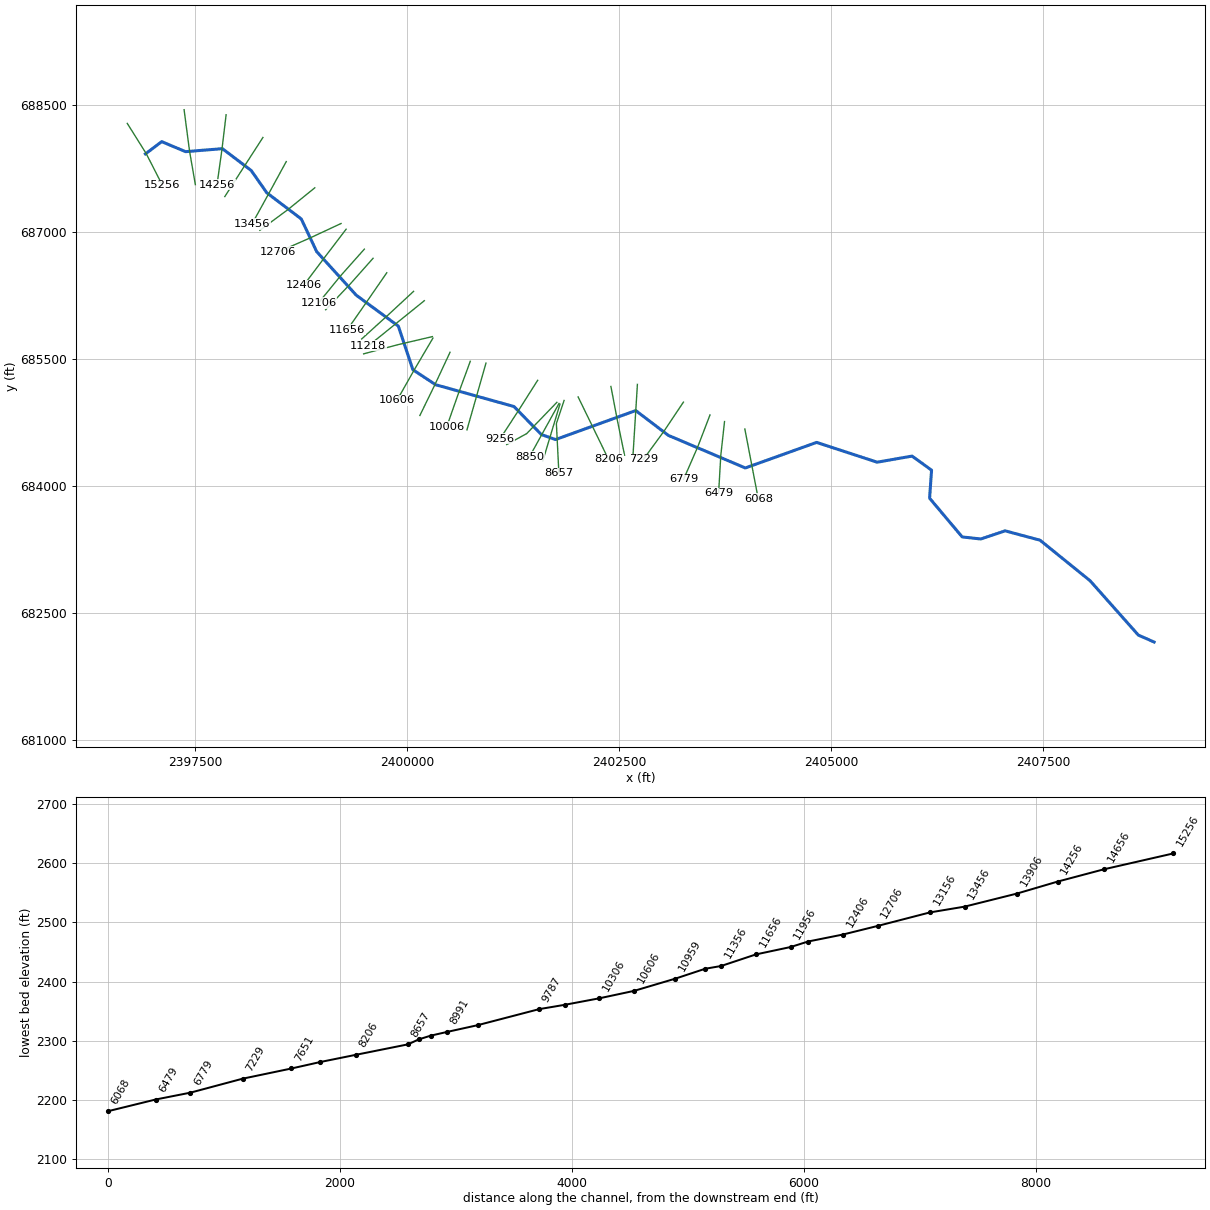
--- HORSCMPRN.prj (project) ---

Proj Title=HORSCMPRN
Current Plan=p01
Default Exp/Contr=0,0
English Units
Geom File=g01
Flow File=f01
Plan File=p01
BEGIN DESCRIPTION:
Stream Name: Horsecamp Run
Flood Zone: Approximate
Pendleton County, West Virginia
HEC-RAS Version: 5.0.7
Hydrology Method:
Regression equation
END DESCRIPTION:
DSS Export Rating Curves= 0
DSS Export Rating Curve Sorted= 0
DSS Export Volume Flow Curves= 0
DXF OffsetX= 0
DXF OffsetY= 0
DXF ScaleX= 0
DXF ScaleY= 0

--- HORSCMPRN.p01 (plan) ---

Plan Title=Floodplain
Program Version=5.07
Short Identifier=Floodplain
Geom File=g01
Flow File=f01
Subcritical Flow
K Sum by GR= 0
Std Step Tol= 0.01
Critical Tol= 0.01
Num of Std Step Trials= 20
Max Error Tol= 0.3
Flow Tol Ratio= 0.001
Split Flow NTrial= 30
Split Flow Tol= 0.02
Split Flow Ratio= 0.02
Log Output Level= 0
Friction Slope Method= 1
Unsteady Friction Slope Method= 2
Unsteady Bridges Friction Slope Method= 1
Parabolic Critical Depth
Global Vel Dist= 0 , 0 , 0
Global Log Level= 0
CheckData=False
Encroach Param=-1 ,0,0, 0
Mapping Interval=1HOUR
Computation Time Step Use Courant=        0
Computation Time Step Use Time Series=    0
Computation Time Step Count To Double=0
Computation Time Step Max Doubling=0
Computation Time Step Max Halving=0
Computation Time Step Residence Courant=0
Run HTab= 0
Run UNet= 0
Run Sediment= 0
Run PostProcess= 0
Run WQNet= 0
Run RASMapper= 0
UNET Theta= 0
UNET Theta Warmup= 0
UNET ZTol= 0
UNET ZSATol= 0
UNET MxIter= 0
UNET Max Iter WO Improvement= 0
UNET MaxInSteps= 0
UNET DtIC= 0
UNET DtMin= 0
UNET MaxCRTS= 0
UNET WFStab= 0
UNET SFStab= 0
UNET WFX= 1
UNET SFX= 1
UNET 1D Methodology=Finite Difference
UNET DSS MLevel= 1
UNET Pardiso=0
UNET DZMax Abort= 0
UNET Use Existing IB Tables= 0
UNET Froude Reduction=False
UNET Froude Limit= 0
UNET Froude Power= 0
UNET D1 Cores= 0
UNET D2 Coriolis=0
UNET D2 Cores= 0
UNET D2 Theta= 1
UNET D2 Theta Warmup= 1
UNET D2 Z Tol= 0.01
UNET D2 Volume Tol= 0.01
UNET D2 Max Iterations= 20
UNET D2 Equation= 0
UNET D2 RampUpFraction=0.1
UNET D2 TimeSlices= 1
UNET D2 BCVolumeCheck=0
UNET D1D2 MaxIter= 0
UNET D1D2 ZTol=0.01
UNET D1D2 QTol=0.1
UNET D1D2 MinQTol=1
Write IC File= 0
Write IC File at Fixed DateTime=0
Write IC File at Sim End=0
Echo Input=False
Echo Parameters=False
Echo Output=False
Write Detailed= 0
HDF Write Warmup=0
HDF Write Time Slices=0
HDF Flush=0
HDF Face Node Velocities=0
HDF Compression= 1
HDF Chunk Size= 1
HDF Spatial Parts= 1
HDF Use Max Rows=0
HDF Fixed Rows= 1
Calibration Method= 0
Calibration Iterations= 20
Calibration Max Change=0.05
Calibration Tolerance=0.2
Calibration Maximum=1.5
Calibration Minimum=0.5
Calibration Optimization Method= 1
WQ AD Non Conservative
WQ ULTIMATE=-1
WQ Max Comp Step=1HOUR
WQ Output Interval=15MIN
WQ Output Selected Increments= 0
WQ Output face flow=0
WQ Output face velocity=0
WQ Output face area=0
WQ Output face dispersion=0
WQ Output cell volume=0
WQ Output cell surface area=0
WQ Output cell continuity=0
WQ Output cumulative cell continuity=0
WQ Output face conc=0
WQ Output face dconc_dx=0
WQ Output face courant=0
WQ Output face peclet=0
WQ Output face adv mass=0
WQ Output face disp mass=0
WQ Output cell mass=0
WQ Output cell source sink temp=0
WQ Output nsm pathways=0
WQ Output nsm derived pathways=0
WQ Output MaxMinRange=-1
WQ Daily Max Min Mean=-1
WQ Daily Range=0
WQ Daily Time=0
WQ Create Restart=0
WQ Fixed Restart=0
WQ System Summary=0
WQ Write To DSS=0
WQ Use Fixed Temperature=0
Sorting and Armoring Iterations= 10
XS Update Threshold= 0.02
Bed Roughness Predictor= 0
Hydraulics Update Threshold= 0.02
Energy Slope Method= 1
Volume Change Method= 1
Sediment Retention Method= 0
XS Weighting Method= 0
Number of US Weighted Cross Sections= 1
Number of DS Weighted Cross Sections= 1
Upstream XS Weight=0
Main XS Weight=1
Downstream XS Weight=0
Number of DS XS's Weighted with US Boundary= 1
Upstream Boundary Weight= 1
Weight of XSs Associated with US Boundary= 0
Number of US XS's Weighted with DS Boundary= 1
Downstream Boundary Weight= 0.5
Weight of XSs Associated with DS Boundary= 0.5
Percentile Method= 0
Sediment Output Level= 3
Mass or Volume Output= 0
Output Increment Type= 1
Profile and TS Output Increment= 1
XS Output Flag= 0
XS Output Increment= 10
Write Gradation File= 0
Read Gradation Hotstart= 0
Write HDF5 File= 1
Write Binary Output= 1
Write DSS Sediment File= 0
SV Curve= 0
Specific Gage Flag= 0

--- HORSCMPRN.f01 (steady flow) ---

Flow Title=Flows
Program Version=5.07
Number of Profiles= 6
Profile Names=P100yr,P10yr,P25yr,P50yr,P500yr,P101yr
River Rch & RM=HORSCMPRN,Main            ,15256
     583     273     386     482     855     710
River Rch & RM=HORSCMPRN,Main            ,14256
     648     303     428     535     952     789
River Rch & RM=HORSCMPRN,Main            ,13156
     737     344     486     608    1083     897
River Rch & RM=HORSCMPRN,Main            ,11356
     822     382     542     678    1209    1000
River Rch & RM=HORSCMPRN,Main            ,8657
     921     428     607     759    1357    1121
River Rch & RM=HORSCMPRN,Main            ,4979
    1160     537     763     955    1713    1412
River Rch & RM=HORSCMPRN,Main            ,3029
    1709     786    1120    1405    2533    2080
Boundary for River Rch & Prof#=HORSCMPRN,Main            , 1
Up Type= 0
Dn Type= 3
Dn Slope=0.03986
Boundary for River Rch & Prof#=HORSCMPRN,Main            , 2
Up Type= 0
Dn Type= 3
Dn Slope=0.03986
Boundary for River Rch & Prof#=HORSCMPRN,Main            , 3
Up Type= 0
Dn Type= 3
Dn Slope=0.03986
Boundary for River Rch & Prof#=HORSCMPRN,Main            , 4
Up Type= 0
Dn Type= 3
Dn Slope=0.03986
Boundary for River Rch & Prof#=HORSCMPRN,Main            , 5
Up Type= 0
Dn Type= 3
Dn Slope=0.03986
Boundary for River Rch & Prof#=HORSCMPRN,Main            , 6
Up Type= 0
Dn Type= 3
Dn Slope=0.03986
DSS Import GetInterval= 0
DSS Import GetPeak= 0
DSS Import FillOption= 0

--- HORSCMPRN.g01 (geometry) ---

Geom Title=Geometry
Program Version=5.07

River Reach=HORSCMPRN       ,Main
Reach XY= 30
     2396909.955      687925.277     2397101.842        688070.2
     2397383.648      687951.831     2397818.089       687987.21
     2398157.736      687729.458     2398341.601      687466.586
     2398748.733      687157.169     2398930.162      686772.029
      2399397.39      686257.155     2399893.623      685892.229
     2400065.161       685377.59     2400334.018       685200.09
      2401258.43      684942.684     2401580.471      684612.444
     2401748.122       684552.652402694.89282984684894.940459098
     2403080.205      684601.738     2403987.748       684217.33
     2404828.836      684519.143     2405543.102      684285.532
     2405954.481       684357.47     2406184.961      684191.736
        2406162.      683860.261     2406546.363      683403.057
     2406766.221      683378.832     2407052.886      683475.144
     2407465.134      683364.438     2408055.572      682885.743
     2408624.581      682244.399     2408810.432      682162.361

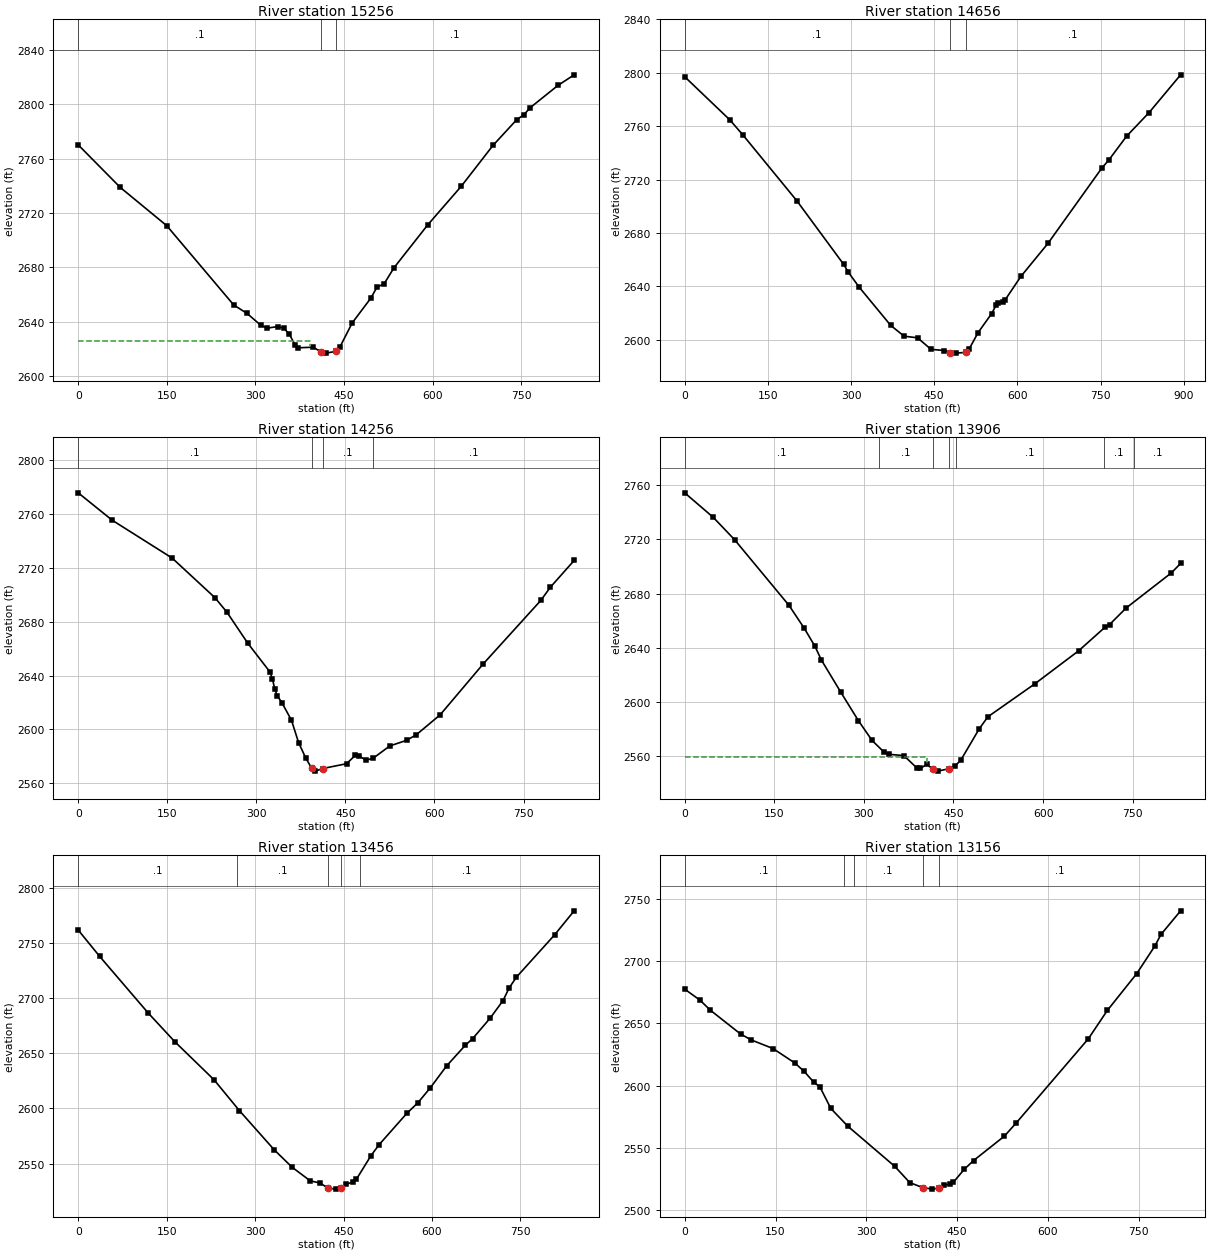
Type RM Length L Ch R = 1 ,15256   ,600,600,600
XS GIS Cut Line= 3
2396695.47353899688285.759538988     2396917.671      687931.637
     2397109.489      687556.535
#Sta/Elev= 30
       0 2770.23    71.2 2738.87   149.8 2710.71   263.1 2652.33   285.9 2646.02
   309.1 2637.33   319.8 2635.23   338.1 2636.42   348.1 2635.11   357.6 2630.61
     367  2622.8   371.7 2620.75   397.5  2621.2   410.52617.937   418.9 2616.83
   436.9 2618.17   443.2 2621.57   463.8 2639.11   495.3 2657.34   505.6 2665.39
   517.7 2667.85   534.6 2679.78   591.8 2711.41   648.3 2739.71   701.9 2769.76
   742.4 2788.87   754.3 2792.38   764.8 2797.54   811.8 2813.95   839.4 2821.81
#Mann= 3 ,-1 , 0
       0      .1       0   410.5    .045       0   436.9      .1       0
#XS Ineff= 2 , 0
          391.81 2626.11
Permanent Ineff=
       F       F
Bank Sta=410.5,436.9
XS Rating Curve= 0 ,0
Exp/Cntr=0.3,0.1

Type RM Length L Ch R = 1 ,14656   ,399.7,399.7,399.7
XS GIS Cut Line= 3
 2397366.0344726688447.353603212     2397430.107       687959.88
     2397498.877      687562.938
#Sta/Elev= 30
       0 2797.05    81.2 2764.82   105.4 2753.23   202.2 2704.15   286.9 2656.36
     295 2650.63   314.8 2639.31   371.6 2610.71   395.8  2602.6     420 2601.41
   444.3 2592.76   468.5 2591.86   478.1 2590.21   488.6 2589.92   506.8 2590.44
   508.9 2590.58     513 2592.95   529.2 2605.29   553.6  2619.5   561.7 2625.81
   565.7 2627.66   573.9 2628.04   577.9 2629.76   606.3 2647.35   655.1 2672.09
   752.5 2728.67   764.7 2734.46   797.1 2752.51   837.7 2770.23   894.5 2798.48
#Mann= 3 ,-1 , 0
       0      .1       0   478.1    .045       0   506.8      .1       0
Bank Sta=478.1,506.8
XS Rating Curve= 0 ,0
Exp/Cntr=0.3,0.1

Type RM Length L Ch R = 1 ,14256   ,350.3,350.3,350.3
XS GIS Cut Line= 3
2397861.77195625688387.5975217672397813.71095625687985.842521767
2397754.29080481687559.243521767
#Sta/Elev= 30
       0 2775.76    57.1 2755.46   158.1 2727.35   230.3 2697.88   250.5 2687.11
   285.6 2664.08     323  2642.7     327 2637.68   331.1 2630.06   335.1 2625.14
   343.1  2619.9   359.2 2606.86   371.3  2590.1   383.4 2578.67   393.4 2571.08
   399.5 2569.08   411.6    2571     452 2574.58   466.6 2580.77   472.2 2580.67
   484.3 2577.25   496.4 2578.53   524.7 2587.76     553 2591.94   569.4 2596.08
   609.5 2610.84   682.2 2648.73   779.2 2695.88   795.3 2705.69   835.3 2725.53
#Mann= 4 ,-1 , 0
       0      .1       0   393.4    .045       0   411.6      .1       0
   496.4      .1       0
Bank Sta=393.4,411.6
XS Rating Curve= 0 ,0
Exp/Cntr=0.3,0.1

Type RM Length L Ch R = 1 ,13906   ,450,450,450
XS GIS Cut Line= 3
     2398296.064      688119.226     2398067.353      687764.926
     2397846.358      687421.397
#Sta/Elev= 30
       0 2754.48      48  2736.3    83.6  2719.8   174.8 2671.24   200.4 2654.23
   218.2 2640.98   228.9  2630.9   261.6 2606.98   290.8 2586.13   313.7 2571.51
   334.3 2562.63   342.6 2561.24     367  2560.3   388.9 2551.07   394.7 2550.84
   405.1  2553.8   415.5 2550.34   423.6 2548.84   443.2 2550.68   452.4 2552.59
   462.2 2556.93   493.1 2580.11   507.6    2589   585.7 2613.19   659.4 2637.73
   703.8 2655.23   711.2 2657.13   739.1 2669.42   814.7 2695.33   830.2  2702.3
#Mann= 7 ,-1 , 0
       0      .1       0  325.69      .1       0   415.5    .045       0
   443.2      .1       0  453.41      .1       0  702.04      .1       0
  752.57      .1       0
#XS Ineff= 2 , 0
          405.23 2559.07
Permanent Ineff=
       F       F
Bank Sta=415.5,443.2
XS Rating Curve= 0 ,0
Exp/Cntr=0.3,0.1

Type RM Length L Ch R = 1 ,13456   ,300,300,300
XS GIS Cut Line= 3
2398571.33428389687834.757904818     2398363.686      687454.404
     2398166.689      687097.281
#Sta/Elev= 30
       0 2761.73    36.3  2737.9   118.3 2686.74   163.9 2660.44   230.3 2625.99
   273.3 2598.05   332.5 2562.42   362.9 2546.61   393.6 2534.28     410 2532.39
   423.7 2527.68   437.4 2526.79   446.5  2527.8   454.3 2531.08   466.1 2533.37
     472 2535.87   496.7 2557.25   510.4 2567.12   557.3 2595.46   576.1 2605.08
   597.2 2618.65     625  2638.6   656.6 2657.27   669.2 2663.35   698.7 2681.83
   720.6 2697.79     731  2709.3   743.4 2719.09     808 2757.34   841.2 2779.16
#Mann= 5 ,-1 , 0
       0      .1       0  269.72      .1       0   423.7    .045       0
   446.5      .1       0  477.12      .1       0
Bank Sta=423.7,446.5
XS Rating Curve= 0 ,0
Exp/Cntr=0.3,0.1

Type RM Length L Ch R = 1 ,13156   ,450,450,450
XS GIS Cut Line= 3
2398908.14519254687525.012210087     2398589.284      687266.577
     2398260.608       687023.68
#Sta/Elev= 30
       0 2677.51    25.3 2668.67    42.3 2660.64    92.3  2641.5   109.9 2636.75
     146  2629.8   181.7 2618.29   197.5 2611.43     213 2602.86   223.2 2599.14
   241.4 2581.71   269.5 2567.44   346.8 2535.31   371.8 2522.19   393.1 2518.19
   409.2 2516.96   420.6 2517.94   428.5 2520.42   438.5 2520.75   443.6  2522.4
   462.1 2533.07   477.2 2539.93     528 2559.48   547.9 2570.28   666.6 2637.62
     698 2660.38   746.7 2690.04   776.7 2712.26   786.6 2721.39   819.1 2740.39
#Mann= 5 ,-1 , 0
       0      .1       0  262.32      .1       0  278.94      .1       0
   393.1    .045       0   420.6      .1       0
Bank Sta=393.1,420.6
XS Rating Curve= 0 ,0
Exp/Cntr=0.3,0.1

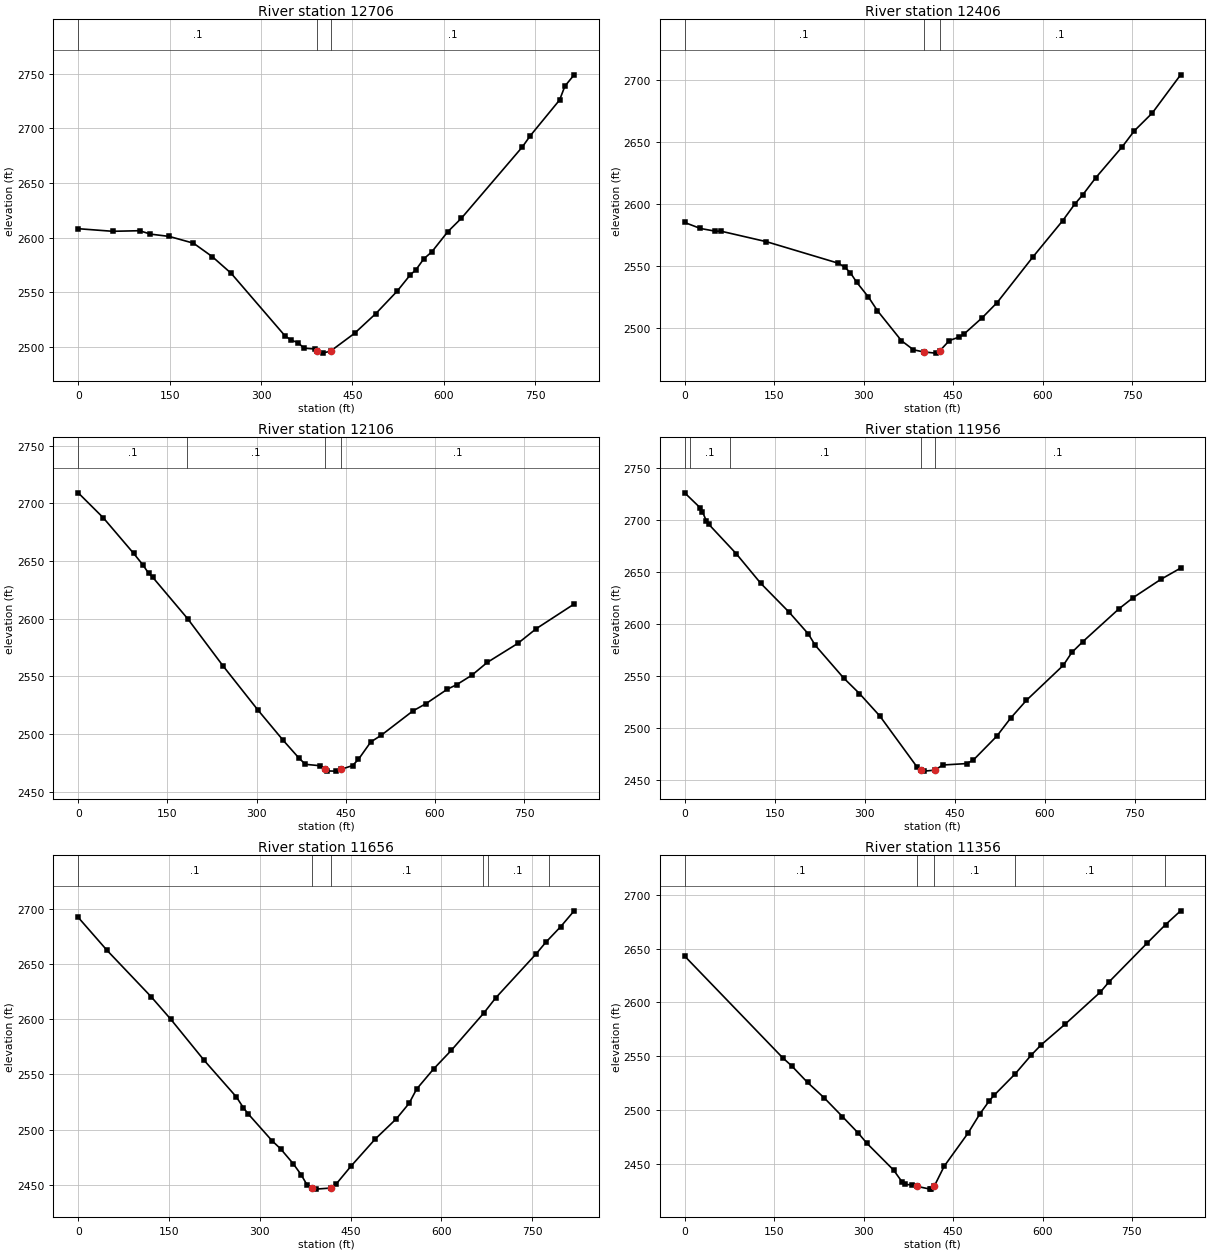
Type RM Length L Ch R = 1 ,12706   ,300,300,300
XS GIS Cut Line= 3
2399218.06108492687103.625934117     2398851.684      686932.619
     2398476.824       686768.02
#Sta/Elev= 30
       0 2608.06    56.6 2605.68   100.8 2606.22   118.4 2603.11   149.3 2600.99
   189.1  2594.8     220 2582.45   250.9 2567.23   339.1 2510.06   349.1 2506.08
   361.2 2503.59     370  2498.7   387.7 2497.92   392.1  2496.2   400.9 2494.12
   414.1 2495.99   453.4 2512.27   488.4 2530.38   523.3 2550.87   545.1 2565.98
   553.9 2570.31   567.2 2580.58   580.1 2586.81   606.3 2605.26   628.7 2617.64
   728.6 2682.86   741.7 2693.18   789.8 2725.91   798.5  2738.6   813.7 2748.97
#Mann= 3 ,-1 , 0
       0      .1       0   392.1    .045       0   414.1      .1       0
Bank Sta=392.1,414.1
XS Rating Curve= 0 ,0
Exp/Cntr=0.3,0.1

Type RM Length L Ch R = 1 ,12406   ,300,300,300
XS GIS Cut Line= 3
     2399277.545      687035.926     2399028.661      686709.288
     2398776.152        686372.9
#Sta/Elev= 30
       0 2585.16    26.4 2580.32    50.8 2578.19    61.6 2578.05   137.1 2569.64
   257.8  2552.2   268.6 2548.94   277.9 2544.43   288.1 2536.97   308.1 2524.83
   323.1 2513.84   363.4 2489.57   383.5 2482.22   400.6 2480.51   420.5 2479.54
   427.2 2481.17   443.7 2489.73   460.5 2492.61   468.7 2495.18   498.7 2508.15
   523.7  2520.4   583.7  2557.3   633.7 2586.68   653.7 2599.94     667 2607.37
   688.7 2621.13   733.7 2646.54   753.7 2659.27   783.8 2673.67   831.3 2704.55
#Mann= 3 ,-1 , 0
       0      .1       0   400.6    .045       0   427.2      .1       0
Bank Sta=400.6,427.2
XS Rating Curve= 0 ,0
Exp/Cntr=0.3,0.1

Type RM Length L Ch R = 1 ,12106   ,150,150,150
XS GIS Cut Line= 3
2399492.55281184 686800.40038509     2399208.789      686481.606
     2398951.585      686165.498
#Sta/Elev= 30
       0 2709.04      42 2687.51    93.1 2656.63   109.1 2646.37   118.5 2639.24
   125.2 2635.91   184.1 2599.91   243.2 2559.26   301.9 2520.98   344.7 2494.52
   371.5 2478.98   382.2 2473.65   407.5 2472.41   414.4 2469.26   418.8  2467.9
     433 2467.75   442.7 2469.39   461.5 2472.57   471.5 2478.02   492.2 2493.05
   509.8 2498.86   563.1 2519.96     585 2526.24   621.1 2538.82   636.6 2542.68
   662.3 2550.94   688.1    2562   739.7 2578.55   770.6 2591.27   834.3 2612.63
#Mann= 4 ,-1 , 0
       0      .1       0  182.68      .1       0   414.4    .045       0
   442.7      .1       0
Bank Sta=414.4,442.7
XS Rating Curve= 0 ,0
Exp/Cntr=0.3,0.1

Type RM Length L Ch R = 1 ,11956   ,300,300,300
XS GIS Cut Line= 3
      2399595.62      686693.038     2399323.799      686386.781
2399036.39245241686084.854641946
#Sta/Elev= 30
       0  2725.9    25.4 2711.76    29.6 2707.71    36.1 2698.92    40.3 2695.56
    85.7 2667.53   126.8  2638.9     174 2611.19   206.1 2590.24   217.5  2579.4
   264.9 2547.93   291.2 2533.02   325.2 2511.39     387 2462.56     393 2459.11
   398.8 2458.46   416.8 2459.39     430 2464.33   469.6 2465.71   480.9 2469.09
   519.8 2491.92   543.1 2509.41   569.5 2526.58   630.8 2560.12     645 2572.48
   663.4 2582.89   724.1 2614.72   747.5 2625.29   793.9 2642.95   826.3 2653.56
#Mann= 5 ,-1 , 0
       0      .1       0    8.22      .1       0   75.19      .1       0
     393    .045       0   416.8      .1       0
Bank Sta=393,416.8
XS Rating Curve= 0 ,0
Exp/Cntr=0.3,0.1

Type RM Length L Ch R = 1 ,11656   ,300,300,300
XS GIS Cut Line= 3
     2399757.502      686522.108      2399524.94      686184.672
     2399290.897      685848.378
#Sta/Elev= 30
       0 2692.51    47.6 2662.59   120.5 2620.51   152.9 2600.09   207.9 2562.91
   261.4 2529.53   272.7 2519.96   280.8 2514.23   320.6 2489.64   334.3 2482.57
   355.2 2469.04   368.3 2459.05     378 2449.88   385.5 2447.05   392.5 2445.91
   417.32446.891   426.6 2450.77     451  2466.9   490.7 2491.34   525.7 2509.73
   546.7 2523.71   559.2  2536.7   587.4 2555.05   616.7 2571.96   670.3 2605.76
   689.8 2619.41   756.8 2659.44   772.6 2669.88     797 2683.92   819.5 2698.45
#Mann= 6 ,-1 , 0
       0      .1       0   385.5    .045       0   417.3      .1       0
  668.85      .1       0  676.43      .1       0  777.37      .1       0
Bank Sta=385.5,417.3
XS Rating Curve= 0 ,0
Exp/Cntr=0.3,0.1

Type RM Length L Ch R = 1 ,11356   ,138.2,138.2,138.2
XS GIS Cut Line= 3
2400074.05539386686302.778006578     2399776.825      686026.834
     2399461.412      685740.445
#Sta/Elev= 30
       0 2642.97   164.4 2548.42   179.2 2541.04     206 2525.51   233.8 2511.26
   264.4 2493.82     291 2478.46   305.5 2468.98   350.4 2443.99   364.7 2432.87
   370.2 2430.66     382 2430.25     390 2428.86   411.4 2426.32   413.8 2426.49
   418.3 2428.81   435.2 2447.65     475 2478.27   494.7    2496     511 2508.61
   518.5 2513.41   554.3 2533.56   581.3 2551.05   597.5 2560.34   637.6 2579.52
   697.1 2609.58   710.9 2618.62   775.1 2654.88   806.3 2672.24   831.6 2685.09
#Mann= 5 ,-1 , 0
       0      .1       0     390    .045       0   418.3      .1       0
  554.09      .1       0  804.84      .1       0
Bank Sta=390,418.3
XS Rating Curve= 0 ,0
Exp/Cntr=0.3,0.1

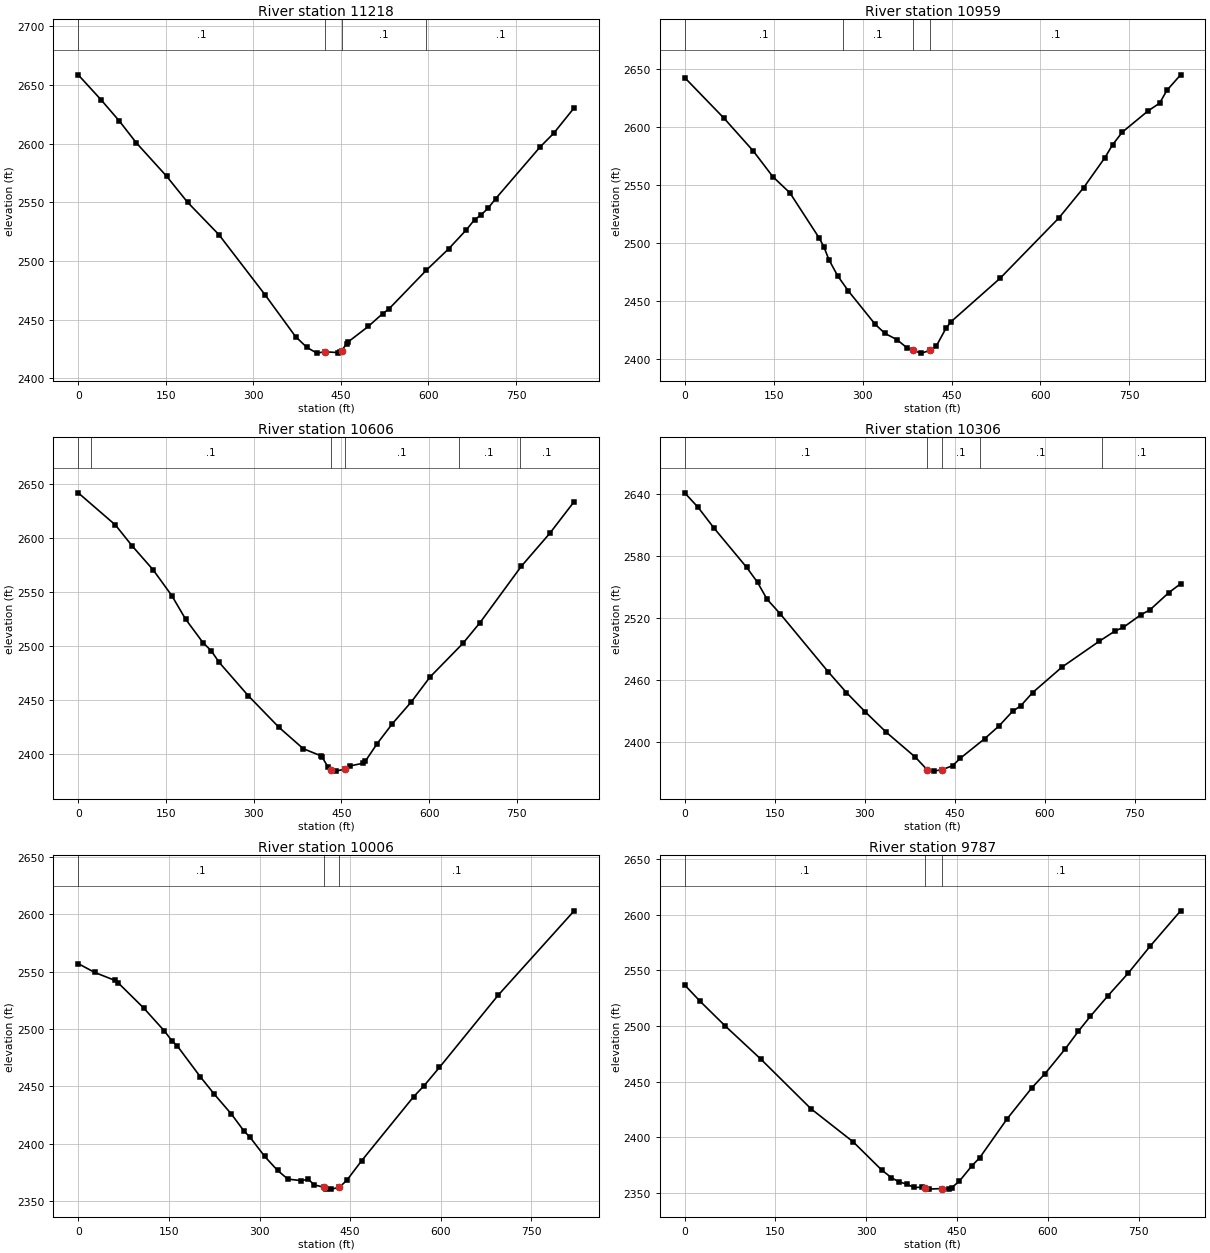
Type RM Length L Ch R = 1 ,11218   ,258.7,258.7,258.7
XS GIS Cut Line= 2
2400200.43013394686192.0767673272399539.47606577685658.401016343
#Sta/Elev= 30
       0 2658.71      39 2637.51    70.3 2619.43    99.8 2600.61   151.3 2572.38
   187.2  2550.2     241 2522.52   320.3 2471.14   372.3 2435.67   391.7 2426.49
   408.8 2421.61   422.52422.813   444.3 2422.06   448.6 2422.51   451.62423.795
   459.7 2429.79   462.8 2431.32     497 2444.41   521.4 2455.24   531.7 2458.98
   596.5 2492.33   634.5 2510.45   664.8 2526.64     679 2535.35   689.6 2539.12
   702.3 2545.21     715 2553.18   791.4 2597.37   814.5 2608.93   849.5 2630.59
#Mann= 4 ,-1 , 0
       0      .1       0   422.5    .045       0   451.6      .1       0
   596.5      .1       0
Bank Sta=422.5,451.6
XS Rating Curve= 0 ,0
Exp/Cntr(USF)=0,0
Exp/Cntr=0.3,0.1

Type RM Length L Ch R = 1 ,10959   ,353.1,353.1,353.1
XS GIS Cut Line= 3
2400295.49204539685768.1865571552399889.87544363685673.180576889
2399484.45944363685564.780576889
#Sta/Elev= 30
       0 2642.75    66.5 2607.55   115.8 2579.27   148.7 2557.14   177.4 2543.22
   226.7 2504.31   234.7 2496.62   243.2 2485.55     258 2471.51     276 2458.49
   321.2 2429.71   337.6 2421.85   357.9 2416.43   374.8 2409.41   384.5  2407.1
   399.3 2404.79   414.4 2407.23     424 2410.61   440.5 2426.14   448.8 2431.75
   531.6 2469.28     631 2521.52   672.6 2547.58   708.5  2573.5   721.6 2584.76
   737.9  2595.6   781.6 2614.07   800.8 2620.59   813.2 2631.75   836.3 2645.13
#Mann= 4 ,-1 , 0
       0      .1       0  267.55      .1       0   384.5    .045       0
   414.4      .1       0
Bank Sta=384.5,414.4
XS Rating Curve= 0 ,0
Exp/Cntr=0.3,0.1

Type RM Length L Ch R = 1 ,10606   ,300,300,300
XS GIS Cut Line= 3
  2400302.114171685750.697545938     2400078.534      685370.785
     2399878.188      685016.249
#Sta/Elev= 30
       0 2642.08    63.7 2612.23    92.6 2592.66     128  2570.8   160.1 2546.77
   183.5 2525.13   213.3 2503.34   227.5 2495.68   241.1 2484.95   290.6 2454.21
   343.2 2424.86   384.7 2405.07   414.3 2398.57   417.5  2396.9   426.8 2388.32
   431.8 2385.48   440.7 2384.25   456.7 2386.24   464.1 2388.97   486.6 2391.52
   491.2 2393.66     511  2409.6   537.2  2428.2   569.8 2448.53   601.5 2471.41
   657.8  2502.6   687.2 2521.93   757.6 2573.99   806.3 2604.54     848 2633.93
#Mann= 6 ,-1 , 0
       0      .1       0   22.47      .1       0   431.8    .045       0
   456.7      .1       0  650.66      .1       0  754.89      .1       0
Bank Sta=431.8,456.7
XS Rating Curve= 0 ,0
Exp/Cntr=0.3,0.1

Type RM Length L Ch R = 1 ,10306   ,300,300,300
XS GIS Cut Line= 3
     2400503.799      685583.203     2400326.752      685203.701
     2400147.978      684837.092
#Sta/Elev= 30
       0 2641.38    22.4 2627.28    48.9 2607.19   103.4 2569.05   121.4 2554.66
   137.2 2538.33   159.2 2524.11     239 2468.06   269.6  2447.8   300.5 2429.35
   335.8 2409.44   384.4 2385.21   403.9 2373.13   415.2 2371.65   429.2 2373.11
   446.4 2376.87   459.7 2384.26   499.8 2402.97   524.1 2415.54   546.5 2429.61
     560  2434.9   579.9 2447.75   628.8 2472.44   691.1 2497.58   717.8 2507.66
   731.2 2511.01   760.4 2523.21   775.4 2527.92   806.8 2544.56   826.6 2553.28
#Mann= 5 ,-1 , 0
       0      .1       0   403.9    .045       0   429.2      .1       0
   491.4      .1       0  695.57      .1       0
Bank Sta=403.9,429.2
XS Rating Curve= 0 ,0
Exp/Cntr=0.3,0.1

Type RM Length L Ch R = 1 ,10006   ,219.3,219.3,219.3
XS GIS Cut Line= 3
     2400742.542      685476.449     2400598.992      685086.064
2400464.80118377684704.212205701
#Sta/Elev= 30
       0  2556.9    27.2 2549.24    60.3 2542.39    65.6 2540.44   108.2 2518.33
   142.3 2498.45   155.1 2489.71   163.6 2485.47     202 2458.43   225.4 2443.11
   253.5 2425.91   274.4 2411.11   284.6 2405.56   308.5 2389.12   329.8 2376.92
   346.9 2369.32   368.2 2368.03     381 2369.04   390.6 2364.21   406.1  2362.4
   410.8 2360.81   418.6 2360.58     432 2362.08   444.7  2368.4   468.8 2385.15
     555 2441.02   572.4 2450.64   597.7 2466.49   694.7 2529.25   820.7 2602.86
#Mann= 3 ,-1 , 0
       0      .1       0   406.1    .045       0     432      .1       0
Bank Sta=406.1,432
XS Rating Curve= 0 ,0
Exp/Cntr=0.3,0.1

Type RM Length L Ch R = 1 ,9787    ,530.7,530.7,530.7
XS GIS Cut Line= 2
2400927.83779503685455.4333423422400703.55479503684667.463342342
#Sta/Elev= 30
       0 2536.93    25.5 2522.26    67.1 2499.99   125.3 2470.51   208.5 2425.66
   278.3 2395.85   325.4 2370.54   341.6 2363.58   353.8 2359.89   366.5 2357.85
     379 2354.77   391.5 2355.03   396.3 2354.09     404  2353.3   424.5 2353.84
   437.2 2353.64   441.4 2354.69   453.9 2360.55   474.7  2374.4   487.2  2381.4
   532.9 2416.71   573.8 2444.59   595.3 2457.17   628.6 2479.37   650.3 2495.25
   670.1 2508.69   699.3 2527.26     733 2547.72   768.6 2571.62   819.3 2603.64
#Mann= 3 , 0 , 0
       0      .1       0   396.3    .045       0   424.5      .1       0
Bank Sta=396.3,424.5
XS Rating Curve= 0 ,0
Exp/Cntr=0.3,0.1

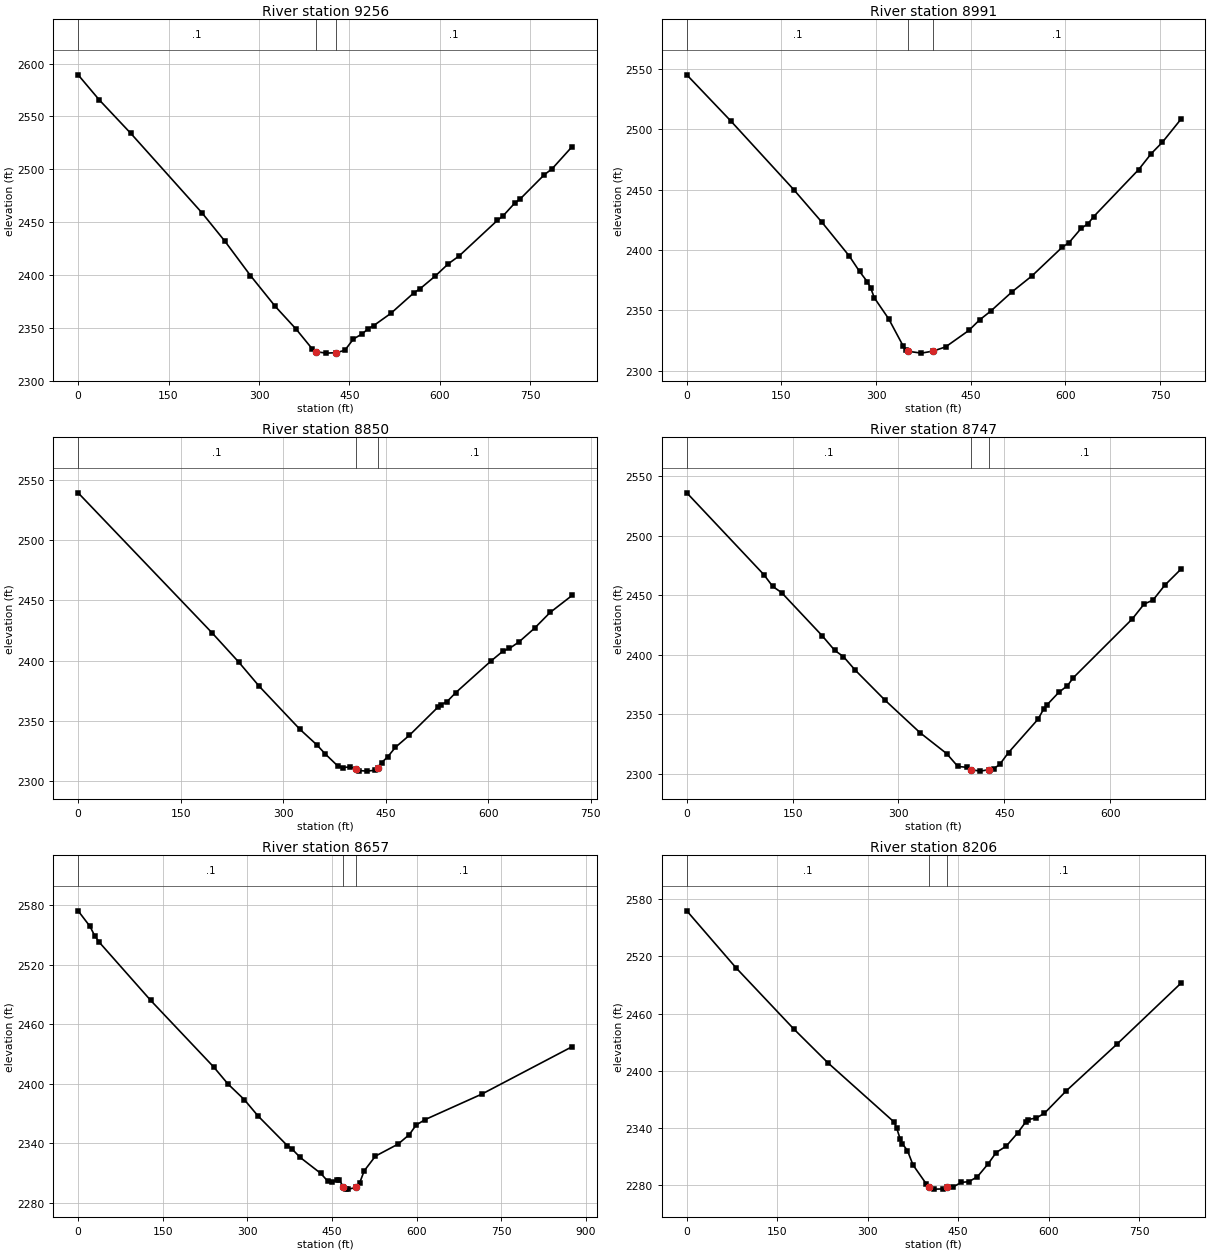
Type RM Length L Ch R = 1 ,9256    ,265.3,265.3,265.3
XS GIS Cut Line= 3
     2401537.643      685252.416     2401318.552       684906.61
     2401095.135      684563.023
#Sta/Elev= 30
       0 2589.31      35 2565.65    87.3    2534   205.4 2458.82   243.3 2432.09
   285.9 2399.43   326.8 2370.45   361.7 2348.75   388.7 2329.87   394.8 2327.42
   411.9 2326.14   428.1 2326.56   442.4 2328.83   456.7 2339.55   471.1 2344.31
   481.3 2349.36     490 2352.08   518.8 2363.79   556.9 2383.17   566.5 2386.72
   592.5 2399.11   614.3 2410.77   631.7 2417.91   695.3 2451.65   704.9 2455.98
   723.9 2467.83   733.5  2472.1   773.3  2494.9     786 2500.36   819.2 2521.33
#Mann= 3 ,-1 , 0
       0      .1       0   394.8    .045       0   428.1      .1       0
Bank Sta=394.8,428.1
XS Rating Curve= 0 ,0
Exp/Cntr=0.3,0.1

Type RM Length L Ch R = 1 ,8991    ,140.8,140.8,140.8
XS GIS Cut Line= 3
2401764.69760395684992.8438184192401408.16672802 684622.88706704
     2401172.289      684494.029
#Sta/Elev= 30
       0 2545.21    69.4 2507.17   169.4 2450.13   213.8 2423.28   257.4 2395.13
   273.7 2382.32     286 2373.83   291.3 2368.72   297.1 2360.49   319.9 2343.05
   342.9  2320.5   347.1 2317.22   350.7 2316.15   371.7 2314.65   390.3 2316.34
   410.1 2319.81   446.9 2333.45   463.8 2342.11   481.3 2349.34   515.4 2365.46
   547.2 2378.78   594.4 2402.17   605.6  2406.2   624.8 2417.99   635.7 2421.87
   644.5 2427.66     716 2466.73   735.9 2479.93   753.6 2489.39   782.6 2508.22
#Mann= 3 ,-1 , 0
       0      .1       0   350.7    .045       0   390.3      .1       0
Bank Sta=350.7,390.3
XS Rating Curve= 0 ,0
Exp/Cntr=0.3,0.1

Type RM Length L Ch R = 1 ,8850    ,102.5,102.5,102.5
XS GIS Cut Line= 2
2401789.70927467684978.9220135482401439.77041337684346.814140853
#Sta/Elev= 30
       0    2539   196.1 2422.85   234.7 2398.87   265.2 2378.49   324.7 2342.86
   349.5 2329.96   361.2 2322.74   379.5 2312.78   387.7 2311.32   397.8 2311.86
   406.32310.048   411.5 2308.78   422.7 2308.34   434.4 2309.08   438.32311.085
   443.8 2315.35   452.7 2320.05   464.2 2328.12   484.7  2338.1     526 2361.17
   530.4 2363.26   539.5 2365.86   552.5 2373.46   603.5  2399.4   621.8 2407.95
     631 2410.06   644.7 2415.33   667.6 2426.77   690.4 2439.83   722.5 2453.91
#Mann= 3 ,-1 , 0
       0      .1       0   406.3    .045       0   438.3      .1       0
Bank Sta=406.3,438.3
XS Rating Curve= 0 ,0
Exp/Cntr(USF)=0,0
Exp/Cntr=0.3,0.1

Type RM Length L Ch R = 1 ,8747    ,90.8,90.8,90.8
XS GIS Cut Line= 2
2401800.79888647684971.5289390132401598.72151587684301.223514558
#Sta/Elev= 30
       0 2535.86   109.3 2467.07   121.8 2457.23   134.4 2452.02   191.6 2415.99
   209.6 2403.53   222.1  2398.2   238.8 2386.85   281.4 2361.39   330.7 2334.27
   368.3 2316.78   384.2 2305.98   397.6  2305.2   403.4 2303.14   416.3 2302.04
   428.5 2303.34   435.2 2304.13   443.5 2307.63     456 2317.63   497.8 2345.64
   506.2 2354.55   510.4 2357.61   527.1 2368.11   539.6  2373.9   548.1 2380.66
   631.5 2429.95   648.2  2442.4   660.8 2445.73   677.5 2458.23   700.1 2471.52
#Mann= 3 , 0 , 0
       0      .1       0   403.4    .045       0   428.5      .1       0
Bank Sta=403.4,428.5
XS Rating Curve= 0 ,0
Exp/Cntr(USF)=0,0
Exp/Cntr=0.3,0.1

Type RM Length L Ch R = 1 ,8657    ,450.7,450.7,450.7
XS GIS Cut Line= 3
     2401849.632      685014.786 2401758.5998492684741.118204937
     2401787.999      684154.971
#Sta/Elev= 30
       0 2574.36      21 2558.71    29.4 2549.22    37.8 2542.47   128.7 2483.99
   240.2 2416.95   265.5 2399.82   294.5 2383.99   318.7 2367.62   370.7 2337.66
   378.8 2334.37   393.6 2325.68   429.8 2309.72   442.8 2301.54   450.8 2300.88
   458.9 2303.14   462.9 2302.88   469.9 2296.13   474.9 2293.88   478.9 2293.75
   492.8 2295.41   498.9 2299.92   506.9 2312.14   526.9 2327.04     567 2339.14
     587 2348.77     599 2358.36     615 2363.88   715.2 2389.51   875.3 2437.32
#Mann= 3 ,-1 , 0
       0      .1       0   469.9    .045       0   492.8      .1       0
Bank Sta=469.9,492.8
XS Rating Curve= 0 ,0
Exp/Cntr=0.3,0.1

Type RM Length L Ch R = 1 ,8206    ,309.5,309.5,309.5
XS GIS Cut Line= 3
     2402014.996      685056.191     2402194.147      684687.959
     2402373.298      684319.726
#Sta/Elev= 30
       0 2567.69    81.7 2507.92   177.3 2443.94   234.2 2408.27     344 2346.17
   347.9 2340.25   353.9 2328.35   357.3 2323.73   365.9 2316.37   375.1 2301.34
   397.3 2281.32     4022278.141   410.7    2276     424 2276.18   431.7 2278.01
   441.8 2278.29   455.2 2283.13   467.6 2283.76   481.9 2289.04   499.7 2302.51
     513 2314.36   529.7 2321.09   548.4 2334.68   561.9 2346.33   566.4 2348.97
   579.7 2350.59   593.1 2355.57   629.2    2379   713.2 2427.91     819  2491.6
#Mann= 3 ,-1 , 0
       0      .1       0     402    .045       0   431.7      .1       0
Bank Sta=402,431.7
XS Rating Curve= 0 ,0
Exp/Cntr=0.3,0.1

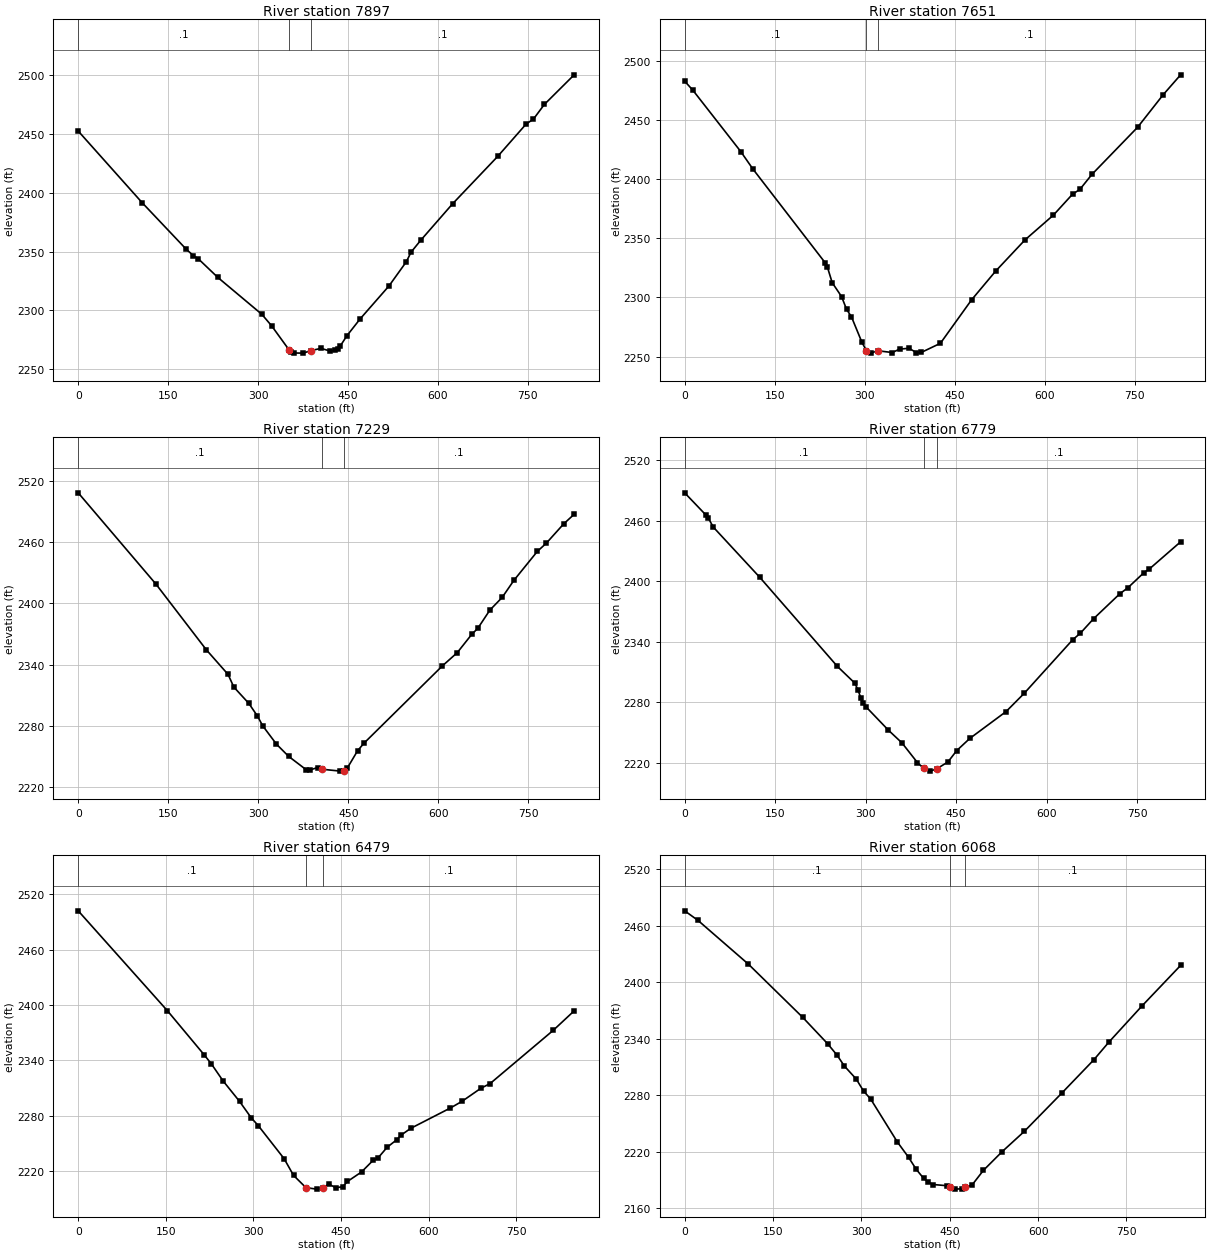
Type RM Length L Ch R = 1 ,7897    ,245.1,245.1,245.1
XS GIS Cut Line= 3
2402401.89950895685179.669735658     2402480.197      684768.837
      2402562.96      684368.408
#Sta/Elev= 30
       0 2452.37   106.7 2391.46     180 2352.04   192.2 2346.45   200.3 2343.82
   232.9 2327.97   306.2 2296.69   322.5 2286.93   352.1 2266.12   355.1 2264.61
   359.1 2263.81   375.4 2263.69   387.9 2265.84     405 2267.74   420.2 2265.42
   428.4 2265.96   432.5 2267.05   436.6 2269.41   448.3 2278.59   470.3 2292.85
   518.2 2320.71   547.3 2341.38     555 2349.41   571.3 2359.62   624.4 2390.59
   699.6 2430.83     747 2458.33   759.2 2462.52   777.4 2474.97   827.1 2500.14
#Mann= 3 , 0 , 0
       0      .1       0   352.1    .045       0   387.9      .1       0
Bank Sta=352.1,387.9
XS Rating Curve= 0 ,0
Exp/Cntr=0.3,0.1

Type RM Length L Ch R = 1 ,7651    ,422,422,422
XS GIS Cut Line= 2
2402714.47888527685204.2192643422402663.30549013684379.435981184
#Sta/Elev= 30
       0 2482.89    13.4 2475.43    93.5 2423.36   113.5 2408.74   233.8 2329.52
   237.8 2325.68   245.8  2312.5   261.4 2300.72   269.8 2289.88   277.9  2283.6
   295.3  2262.1   302.9 2254.94   309.9 2252.88   321.8 2254.88     346 2253.39
     358 2256.26     374    2257   386.1 2253.24   394.1 2253.43   426.1 2261.18
   478.2 2298.04   518.3 2322.32     567 2348.62   614.5 2369.66   646.3 2387.32
   658.6 2391.41   678.6 2404.06   754.8 2443.98   797.2 2471.37   826.4 2488.29
#Mann= 3 , 0 , 0
       0      .1       0   302.9    .045       0   321.8      .1       0
Bank Sta=302.9,321.8
XS Rating Curve= 0 ,0
Exp/Cntr=0.3,0.1

Type RM Length L Ch R = 1 ,7229    ,450,450,450
XS GIS Cut Line= 3
     2403257.348      684994.557     2403029.725      684653.736
2402784.00655214684317.414447855
#Sta/Elev= 30
       0 2508.47   129.5 2418.99   213.5 2354.54   249.7 2330.41   259.3 2318.01
   284.3    2302   298.7 2289.55   307.4 2280.04   330.4 2261.98   350.7 2250.02
   379.4 2237.17   386.4 2236.77   398.8 2239.07   405.4 2237.49   436.9 2235.58
   443.1    2236   448.4 2238.58   465.5 2255.52   475.9 2262.82   606.6 2338.64
   631.6 2351.76   656.1 2369.94   665.8 2375.55   685.9 2393.42   706.5 2405.95
     726 2422.65   765.1 2451.06     780 2459.08     809 2478.04   826.4 2487.43
#Mann= 3 ,-1 , 0
       0      .1       0   405.4    .045       0   443.1      .1       0
Bank Sta=405.4,443.1
XS Rating Curve= 0 ,0
Exp/Cntr=0.3,0.1

Type RM Length L Ch R = 1 ,6779    ,300,300,300
XS GIS Cut Line= 3
     2403570.895       684843.18     2403424.433      684461.641
     2403258.974      684082.684
#Sta/Elev= 30
       0 2487.81    34.6 2466.18    38.9 2463.09    47.4 2453.86   124.6    2404
   253.1  2315.8   282.1 2299.15   287.4  2292.3   291.7 2284.93   295.9  2279.6
   300.2 2275.94   337.8 2252.51   360.2 2239.96   385.9 2220.41   396.42214.579
   407.3 2211.95   418.1 2214.32   436.4 2221.01     451  2232.3   472.7 2244.36
   532.9 2271.02   562.9 2289.08     643 2342.01   656.1 2348.73   677.9 2363.01
   721.6 2387.86   734.7 2393.66   761.4 2408.69   770.6 2412.43   822.2 2439.26
#Mann= 3 ,-1 , 0
       0      .1       0   396.4    .045       0   418.1      .1       0
Bank Sta=396.4,418.1
XS Rating Curve= 0 ,0
Exp/Cntr=0.3,0.1

Type RM Length L Ch R = 1 ,6479    ,411.2,411.2,411.2
XS GIS Cut Line= 3
     2403742.325      684765.503     2403698.054      684361.543
2403672.55018724683919.246491051
#Sta/Elev= 30
       0 2501.92   152.6 2393.78     216 2345.69     228 2336.12   248.1 2317.61
   276.3 2295.44   296.4 2277.58   308.4 2269.13   352.7 2233.29   368.8 2215.24
     390 2201.97   408.2 2200.35   419.6 2201.97   429.1 2205.84   441.1 2201.87
   453.1 2202.95   461.1 2208.63   485.2 2218.93   505.2 2231.63   513.2 2233.94
   529.2 2245.76   545.3 2253.72   553.3 2259.01   569.3 2266.14   637.4 2288.25
   657.4  2295.5   689.5 2309.58   705.5 2314.74   813.6 2372.43   849.4 2393.52
#Mann= 3 ,-1 , 0
       0      .1       0     390    .045       0   419.6      .1       0
Bank Sta=390,419.6
XS Rating Curve= 0 ,0
Exp/Cntr=0.3,0.1

Type RM Length L Ch R = 1 ,6068    ,338.8,338.8,338.8
XS GIS Cut Line= 2
2403982.18387931684677.0177101292404140.82643834683850.122699968
#Sta/Elev= 30
       0 2476.09    22.5 2465.98   108.1  2419.5   200.5 2362.89   242.5 2335.06
   258.8 2322.74     271 2311.35   291.3 2297.41   303.6 2284.77   315.8 2276.18
   361.1 2230.59     380  2214.4   393.2  2201.5   405.5 2192.13   413.5 2187.92
   421.7 2185.44   446.1 2184.11     450 2182.44   458.3 2180.53   470.6 2180.88
   475.7  2182.3   487.6 2184.67   507.2 2200.48   538.8 2220.23   576.5 2241.78
   639.9 2282.28   694.6 2317.84   719.9 2336.44     776  2374.8     842 2418.13
#Mann= 3 ,-1 , 0
       0      .1       0     450    .045       0   475.7      .1       0
Bank Sta=450,475.7
XS Rating Curve= 0 ,0
Exp/Cntr=0.3,0.1