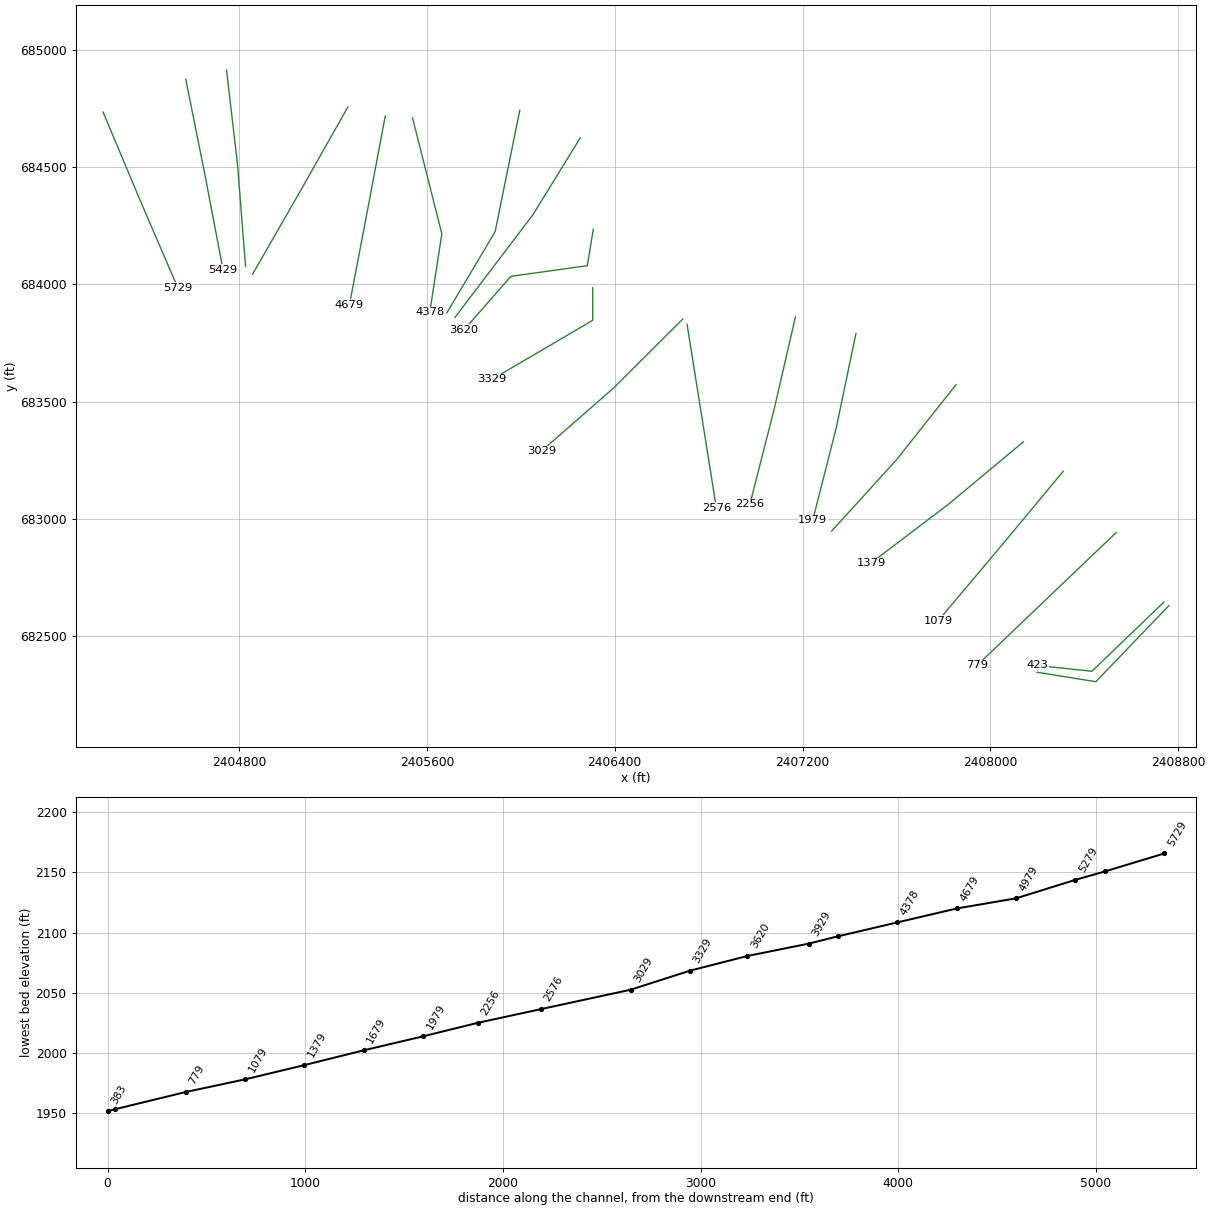
HEC-RAS study HORSCMPRN.prj: HORSCMPRN

--- HORSCMPRN.g01 (geometry) --- (continued)

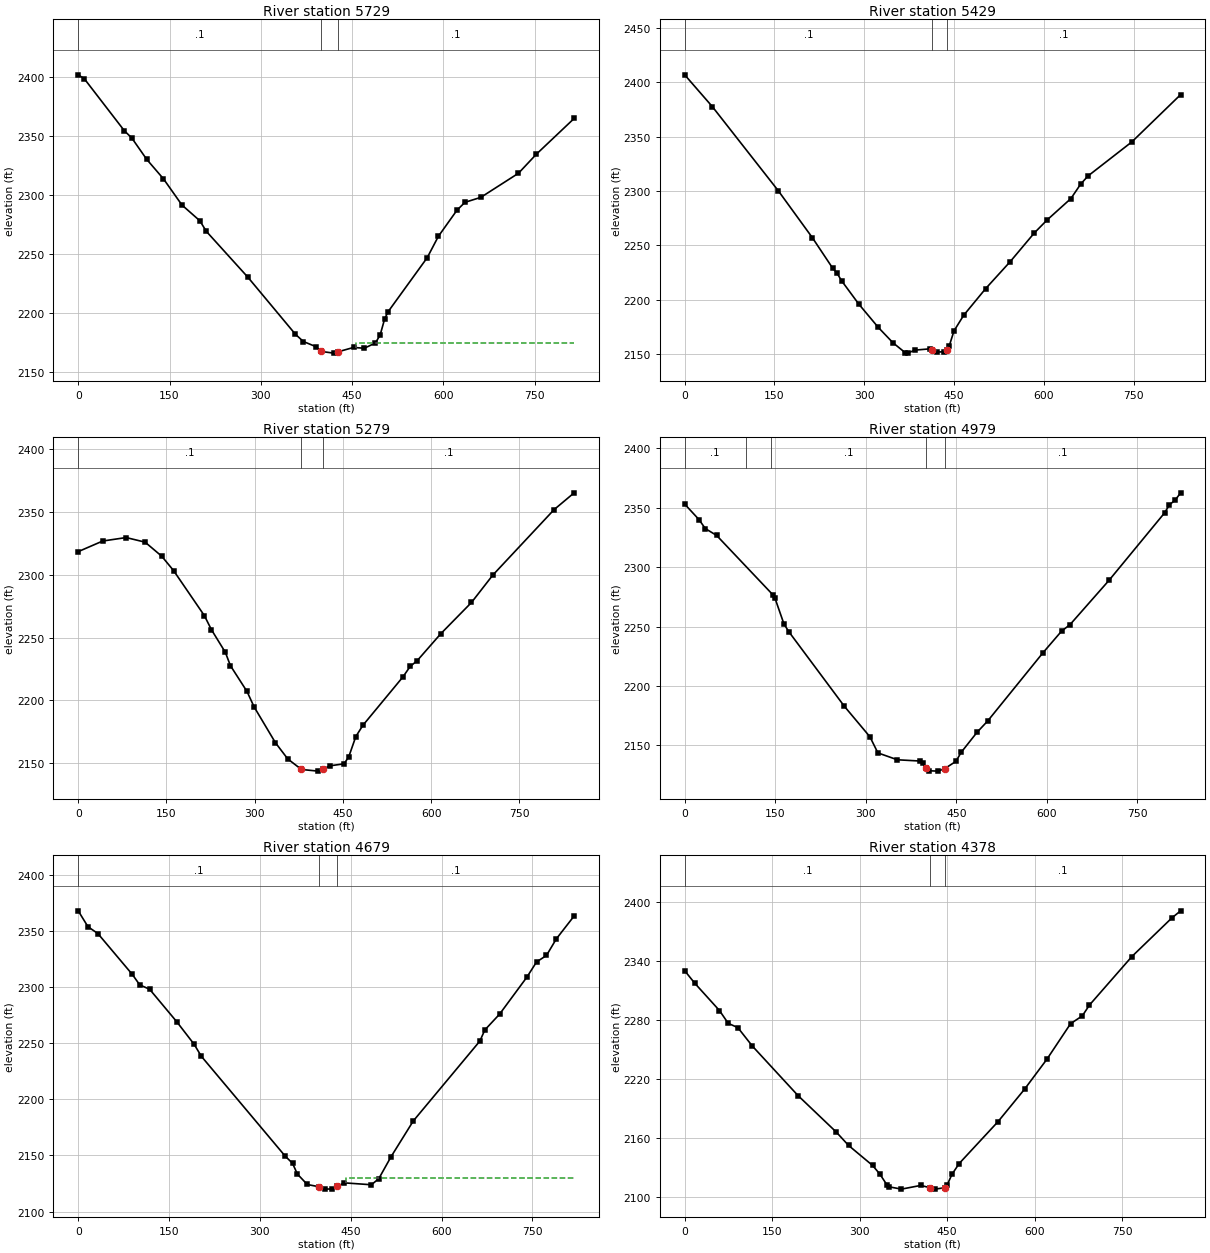
Type RM Length L Ch R = 1 ,5729    ,300,300,300
XS GIS Cut Line= 3
     2404220.647      684736.135     2404379.526      684356.733
2404538.88826078683985.964043427
#Sta/Elev= 30
       0 2402.02      10  2398.7    75.9 2354.49    88.1 2348.34   112.6 2330.21
   140.1 2313.69   170.5 2291.44   199.9 2278.08   210.4 2269.18   278.9 2230.09
   356.9 2181.72     370 2175.56   390.7 2171.18   398.9 2167.19   419.5 2165.71
   427.4  2166.9   452.5 2170.55     470 2169.85   488.3  2174.3   496.1  2181.1
   503.5 2194.71   509.1 2200.81   573.5 2246.79   591.8 2264.88   622.2 2286.96
   635.4 2293.75   661.5 2297.97   723.4 2318.45   752.9 2334.67   814.9 2364.99
#Mann= 3 ,-1 , 0
       0      .1       0   398.9    .045       0   427.4      .1       0
#XS Ineff= 2 , 0
                          455.95         2174.41
Permanent Ineff=
       F       F
Bank Sta=398.9,427.4
XS Rating Curve= 0 ,0
Exp/Cntr=0.3,0.1

Type RM Length L Ch R = 1 ,5429    ,150,150,150
XS GIS Cut Line= 3
2404572.89232164684876.172439085      2404655.19      684464.606
     2404731.638      684062.802
#Sta/Elev= 30
       0 2406.82    46.2 2377.57   156.3 2300.25   213.4 2256.95   247.4 2228.85
   254.2 2224.66   262.4 2217.21   290.9 2195.92   323.6 2174.39     348 2160.34
   368.4 2151.23   372.5 2150.78   384.8 2153.54   409.2  2154.7     414  2153.6
   421.5 2151.78   433.7 2152.02   437.9 2153.32   441.8 2156.91     450 2171.22
   466.2 2185.59   502.9 2210.12     544 2234.98   584.3 2261.39   605.5 2273.24
   645.4 2293.01   661.7 2306.29   674.1 2313.83   747.2 2345.11   828.7 2388.59
#Mann= 3 ,-1 , 0
       0      .1       0     414    .045       0   437.9      .1       0
Bank Sta=414,437.9
XS Rating Curve= 0 ,0
Exp/Cntr=0.3,0.1

Type RM Length L Ch R = 1 ,5279    ,300,300,300
XS GIS Cut Line= 3
      2404746.42       684915.86     2404793.069      684514.981
2404827.43531725684076.867665205
#Sta/Elev= 30
       0 2318.51    41.7 2326.96    81.5 2329.71   113.7 2326.05   141.9 2314.88
   162.1 2303.42   214.4  2267.6   226.5 2256.32   250.1 2238.35   258.7 2227.75
   286.9  2207.2     299  2194.9   335.2 2166.41   356.2 2153.47   379.5 2145.09
   407.7 2143.77   415.7  2145.3     428 2148.02   451.8 2149.57   459.8  2155.1
   471.9 2171.31   483.9 2180.24   552.1 2218.85   564.2 2227.07   576.2 2231.71
   616.3 2253.15   668.5 2278.04   704.6 2299.75   808.9 2351.95     843 2365.32
#Mann= 3 ,-1 , 0
       0      .1       0   379.5    .045       0   415.7      .1       0
Bank Sta=379.5,415.7
XS Rating Curve= 0 ,0
Exp/Cntr=0.3,0.1

Type RM Length L Ch R = 1 ,4979    ,300,300,300
XS GIS Cut Line= 3
     2405263.555      684758.178     2405061.627      684400.175
      2404857.55      684043.772
#Sta/Elev= 30
       0 2353.04    23.6 2340.08    34.2 2332.45    52.9  2326.7   146.9 2276.34
   149.8 2273.64   164.5 2252.19   172.6 2245.68   264.3 2183.14   306.9 2157.33
   320.1 2143.78   352.4 2137.98   389.5 2136.94   394.1 2135.69   400.6 2130.79
   405.3 2128.72   419.9 2128.44   430.9 2130.58   449.4 2136.63     458 2144.16
   484.4  2161.1     502  2170.6   593.9 2228.16   624.5 2246.21   638.4 2251.63
   702.9 2288.81   795.1 2345.64   803.2 2352.48   812.7 2356.39   821.7 2362.52
#Mann= 5 ,-1 , 0
       0      .1       0   101.2      .1       0   142.6      .1       0
   400.6    .045       0   430.9      .1       0
Bank Sta=400.6,430.9
XS Rating Curve= 0 ,0
Exp/Cntr=0.3,0.1

Type RM Length L Ch R = 1 ,4679    ,301.4,301.4,301.4
XS GIS Cut Line= 3
     2405422.445       684718.72     2405346.897      684316.247
     2405270.306      683913.974
#Sta/Elev= 30
       0 2368.02    16.1 2353.86    32.4  2347.8    89.4  2311.3   101.6 2302.02
   117.9 2298.13   162.6 2269.25   191.5 2249.03   203.3  2238.4   341.7 2149.47
   353.9 2143.01     362 2133.36   378.3 2124.12   397.1 2122.15   406.8 2119.99
     419 2120.15   427.2 2122.39   439.4 2125.58   484.2 2123.88   496.4 2129.35
   516.6 2148.85   553.4 2180.78   663.3 2251.95   671.5 2261.85   695.9 2275.97
   740.7 2308.73     757 2322.51   773.3 2328.24   789.6 2343.05     819 2363.45
#Mann= 3 ,-1 , 0
       0      .1       0   397.1    .045       0   427.2      .1       0
#XS Ineff= 2 , 0
                          441.89         2130.08
Permanent Ineff=
       F       F
Bank Sta=397.1,427.2
XS Rating Curve= 0 ,0
Exp/Cntr=0.3,0.1

Type RM Length L Ch R = 1 ,4378    ,298.2,298.2,298.2
XS GIS Cut Line= 3
     2405538.806      684711.3352405663.64577329684215.861604865
     2405612.067      683880.326
#Sta/Elev= 30
       0 2330.41      17 2317.86    59.6 2289.95    74.7  2276.9    91.2 2272.53
     116 2253.84   194.3 2203.52   259.9 2166.44     281 2152.83   322.2 2132.48
   334.6 2123.77     347 2112.55   351.1 2110.71   371.7 2108.42   404.7 2112.17
   421.2 2109.81   429.5 2108.44     446 2109.86   450.1 2112.68   458.3 2123.41
   470.7 2134.46   537.2 2176.94   582.8 2209.98   621.2  2240.5   661.7 2276.56
   681.9 2284.54   694.1 2295.51   766.9 2344.83   835.3 2383.99   850.4 2391.25
#Mann= 3 ,-1 , 0
       0      .1       0   421.2    .045       0     446      .1       0
Bank Sta=421.2,446
XS Rating Curve= 0 ,0
Exp/Cntr=0.3,0.1

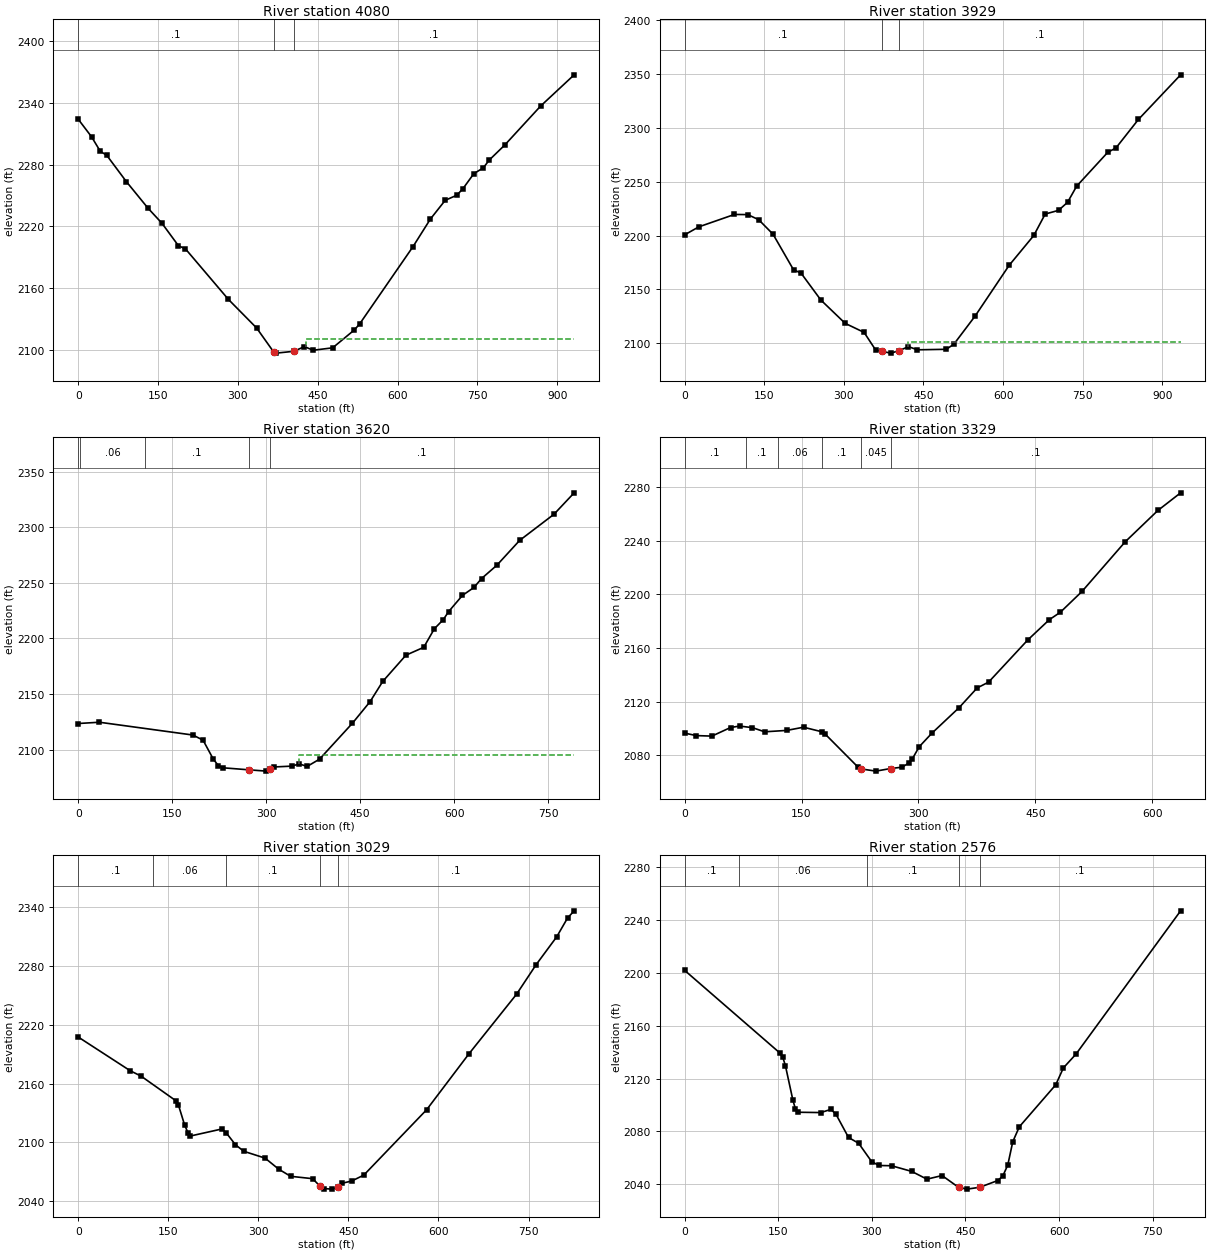
Type RM Length L Ch R = 1 ,4080    ,150.4,150.4,150.4
XS GIS Cut Line= 3
     2405995.597      684743.5062405890.61918908684225.204964204
     2405684.964      683878.545
#Sta/Elev= 30
       0 2324.09      25 2307.07    41.4 2292.99    53.7 2288.98    90.4 2263.54
   131.2 2237.66   157.4 2223.02   188.4 2201.19   201.5 2198.19   282.2 2149.13
   335.3 2121.32   367.9 2097.62     372 2096.95   405.1 2098.72   425.1 2103.28
   441.4 2099.75   478.1 2102.09   518.9 2119.47   528.8 2125.28   629.2 2200.44
   661.7  2227.1   689.6 2245.34   711.4 2250.28   723.1 2256.76   743.5 2271.28
     761 2276.76   772.7  2284.6   801.3  2298.9     869 2336.92   931.9 2367.18
#Mann= 3 ,-1 , 0
       0      .1       0   367.9    .045       0   405.1      .1       0
#XS Ineff= 2 , 0
                          428.37         2110.32
Permanent Ineff=
       F       F
Bank Sta=367.9,405.1
XS Rating Curve= 0 ,0
Exp/Cntr=0.3,0.1

Type RM Length L Ch R = 1 ,3929    ,309,309,309
XS GIS Cut Line= 3
     2406252.952       684625.68     2406051.678      684297.803
     2405719.704      683859.437
#Sta/Elev= 30
       0 2200.65    26.7 2208.04    93.8 2219.55   118.9  2219.4   139.4  2214.7
   166.5 2201.21   205.1 2168.18   219.2 2165.13   256.7 2140.04   302.4 2118.44
   338.1 2110.02     360 2093.59   371.2 2092.44   388.4 2090.77   403.4 2092.92
   421.7 2096.79   438.6 2093.85   493.1 2094.33   507.4 2099.13   547.4 2125.24
   611.5 2172.34   657.9 2200.02   679.4 2219.94   704.5 2223.34   721.5  2230.8
   738.7 2245.83   797.1 2277.15   812.9  2281.4     855 2307.73   934.6 2349.21
#Mann= 3 ,-1 , 0
       0      .1       0   371.2    .045       0   403.4      .1       0
#XS Ineff= 2 , 0
                          419.91         2101.32
Permanent Ineff=
       F       F
Bank Sta=371.2,403.4
XS Rating Curve= 0 ,0
Exp/Cntr=0.3,0.1

Type RM Length L Ch R = 1 ,3620    ,291,291,291
XS GIS Cut Line= 4
2406308.81211981684236.2089048382406283.37324205684080.117922619
2405957.80797654684034.717274097     2405757.553      683805.439
#Sta/Elev= 30
       0  2123.4    33.8 2124.55     183 2113.04   199.2 2108.42   215.3 2091.61
   223.6 2085.47   231.5 2083.55   271.82081.763   300.1 2080.57   305.8 2082.34
   312.3 2084.31   340.5 2085.06   352.6 2087.01   365.4 2084.84     385 2091.33
   437.5 2123.64   465.7 2143.08   485.9 2161.25   522.9 2184.86   551.3 2191.94
   568.3 2208.68   582.5 2216.84     591 2224.07   613.1 2238.66   631.4 2245.77
   643.5 2253.77   667.9 2265.73   704.3 2288.09   759.1 2311.63   791.3 2330.91
#Mann= 5 ,-1 , 0
       0      .1       0    2.82     .06       0  106.61      .1       0
   271.8    .045       0   305.8      .1       0
#XS Ineff= 2 , 0
                          352.24         2094.85
Permanent Ineff=
       F       F
Bank Sta=271.8,305.8
XS Rating Curve= 0 ,0
Exp/Cntr=0.3,0.1

Type RM Length L Ch R = 1 ,3329    ,300,300,300
XS GIS Cut Line= 4
2406306.06465201683985.7676730862406306.56130526683847.016866167
     2406211.772        683791.12405877.62142616683594.793779448
#Sta/Elev= 30
       0 2096.64    14.9 2094.81    34.9 2094.42    58.9 2100.83    70.4 2101.89
    86.9 2100.73   102.6 2097.63   130.9 2098.66   152.5 2101.05   175.7  2097.7
   180.3 2095.92   222.1 2071.51   226.42069.978   245.4 2068.34   264.3 2070.29
   278.9 2071.27   287.7 2074.37   291.7 2077.05     301 2086.53   316.9  2096.4
   352.1  2115.6   375.3 2130.29     390 2134.64   440.2    2166     468 2181.18
     482 2186.63   509.8 2202.14   565.3 2239.15   607.2 2262.47   636.4 2275.62
#Mann= 6 ,-1 , 0
       0      .1       0    78.4      .1       0  119.74     .06       0
   175.7      .1       0   226.4    .045       0   264.3      .1       0
Bank Sta=226.4,264.3
XS Rating Curve= 0 ,0
Exp/Cntr=0.3,0.1

Type RM Length L Ch R = 1 ,3029    ,453.5,453.5,453.5
XS GIS Cut Line= 3
2406689.66179211683852.113189078     2406393.444      683555.871
     2406087.204      683287.685
#Sta/Elev= 30
       0 2207.35    86.6 2173.03   104.8 2167.51   162.5 2142.56     167 2138.01
   177.1    2118   182.7 2110.02   186.8 2106.59   239.3 2113.76   246.2  2110.1
   261.9 2097.71   275.7 2091.07   311.2 2084.11   333.9 2072.86   353.7  2065.6
   390.4 2063.17   403.3 2055.23     409 2053.13   422.5 2052.54   433.2 2055.13
   438.6 2058.38   455.6 2060.81   475.7 2066.83   580.3 2133.34   651.1  2190.5
   730.1 2250.94   762.8 2281.09   796.9 2309.27   815.1 2328.55     826 2335.77
#Mann= 5 ,-1 , 0
       0      .1       0  125.35     .06       0  246.17      .1       0
   403.3    .045       0   433.2      .1       0
Bank Sta=403.3,433.2
XS Rating Curve= 0 ,0
Exp/Cntr=0.3,0.1

Type RM Length L Ch R = 1 ,2576    ,319.7,319.7,319.7
XS GIS Cut Line= 2
2406708.12921637 683830.236544622406833.08376851683045.280083609
#Sta/Elev= 30
       0 2201.69   153.3 2138.99   157.3 2135.96   161.4 2129.79   173.5 2103.49
   177.6  2096.9   181.6 2094.52   218.1 2094.28   234.3 2096.67   242.4 2093.06
   262.6 2075.45   278.8 2071.09   299.5 2057.31   311.2  2054.3   331.5 2054.11
   363.9 2049.82   388.2 2043.97   412.5 2046.69   439.2  2037.7   452.5 2036.44
     473 2037.85   501.6 2042.91   509.7 2046.25   517.8 2054.63   525.8 2072.24
   536.3 2083.54   594.7 2115.27   606.9 2128.02   627.2 2138.49   794.8 2246.69
#Mann= 5 ,-1 , 0
       0      .1       0    86.6     .06       0  291.57      .1       0
   439.2    .045       0     473      .1       0
Bank Sta=439.2,473
XS Rating Curve= 0 ,0
Exp/Cntr=0.3,0.1

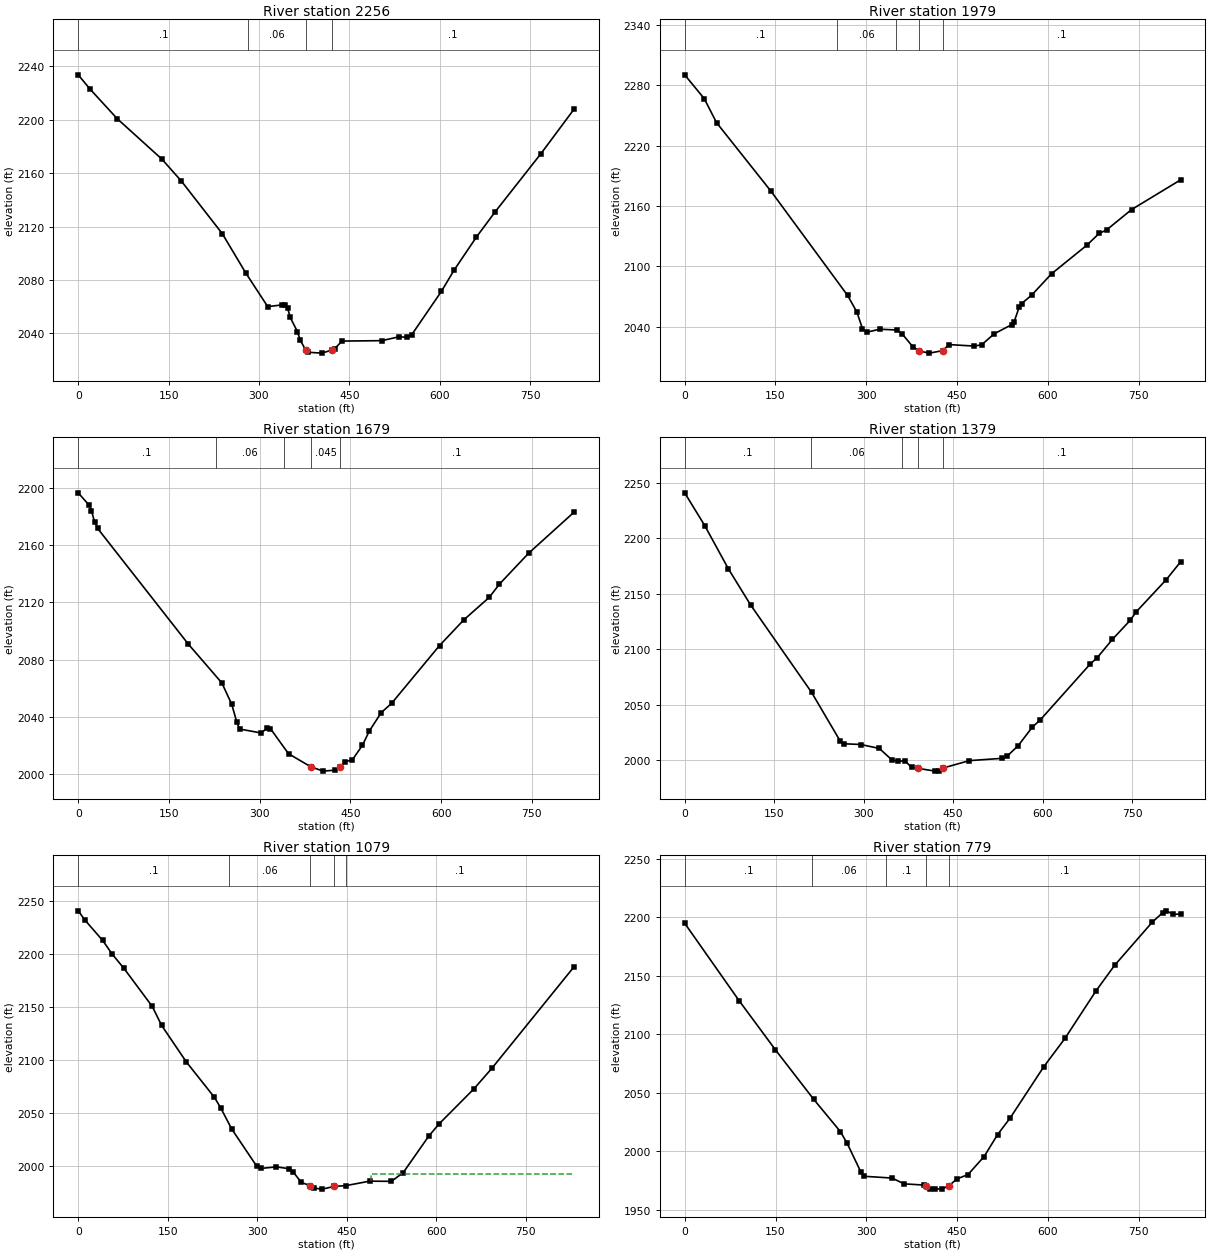
Type RM Length L Ch R = 1 ,2256    ,276.9,276.9,276.9
XS GIS Cut Line= 3
2407169.82259298683861.5250021932407079.23959298683467.127002193
2406975.91473674683061.542436892
#Sta/Elev= 30
       0 2233.75    19.1 2223.32    64.8 2200.81   138.8 2170.56     171  2154.2
   239.2 2114.61   278.4 2084.96   314.6  2059.9   338.5 2061.23   343.3 2061.11
   347.5 2059.15   351.6  2052.1   363.9 2041.17   368.6 2034.74   377.7 2027.24
   381.9 2025.68   404.7 2025.05   420.9 2027.38   425.5 2028.29   437.9 2034.09
   503.9  2034.4   532.9 2037.35   545.3 2036.88   553.5  2038.8     603 2071.45
   623.7 2087.14   660.8    2112   692.3 2131.14   768.2 2174.72   823.2  2208.1
#Mann= 4 ,-1 , 0
       0      .1       0   282.5     .06       0   377.7    .045       0
   420.9      .1       0
Bank Sta=377.7,420.9
XS Rating Curve= 0 ,0
Exp/Cntr=0.3,0.1

Type RM Length L Ch R = 1 ,1979    ,300,300,300
XS GIS Cut Line= 3
     2407427.636      683790.464      2407344.18      683389.621
      2407243.37      682992.368
#Sta/Elev= 30
       0 2290.35    32.3 2266.71    52.7 2242.78   142.6 2174.69   269.2 2071.11
   284.5 2054.64   293.7 2038.17   301.9 2034.76   322.3 2037.61   350.9 2036.78
   358.9 2033.26   377.2 2019.91   387.7 2015.93   404.1 2013.83     426 2016.26
     437 2022.31   478.3 2020.84   490.7 2022.14   511.3 2033.02   540.2 2042.11
   544.3 2045.07   552.6 2059.46   556.7  2063.1   573.2 2071.44   606.2 2092.74
     664 2120.86   684.6 2132.72     697 2136.24   738.3 2156.48   819.3    2186
#Mann= 5 ,-1 , 0
       0      .1       0  251.48     .06       0  349.15      .1       0
   387.7    .045       0     426      .1       0
Bank Sta=387.7,426
XS Rating Curve= 0 ,0
Exp/Cntr=0.3,0.1

Type RM Length L Ch R = 1 ,1679    ,300,300,300
XS GIS Cut Line= 3
     2407854.042      683572.066     2407599.317       683249.97
     2407324.246      682946.884
#Sta/Elev= 30
       0  2196.5    18.2 2187.77    21.9 2184.13      27  2176.2    32.1 2171.65
   182.1 2090.85   237.5 2063.78   253.8 2048.86   262.3 2036.22   266.7 2031.63
   302.2 2028.88   312.6 2032.19   317.7 2031.94   347.7 2014.37   384.8  2005.2
   405.1 2002.23   424.6 2002.91   433.1 2004.86   441.3 2008.83   453.2 2010.11
   469.9 2020.27   481.2 2030.18     501 2043.11     518 2049.49   597.3 2089.88
   637.7 2107.92   679.5  2123.5   696.4 2132.78   744.5 2154.28   819.9 2183.06
#Mann= 5 ,-1 , 0
       0      .1       0  227.93     .06       0     340      .1       0
   384.8    .045       0   433.1      .1       0
Bank Sta=384.8,433.1
XS Rating Curve= 0 ,0
Exp/Cntr=0.3,0.1

Type RM Length L Ch R = 1 ,1379    ,300,300,300
XS GIS Cut Line= 3
     2408141.026      683328.009     2407821.514      683061.196
     2407491.443      682810.058
#Sta/Elev= 30
       0 2240.89    33.7 2211.27    73.4 2172.19   110.3 2139.93   212.6 2060.99
   260.8 2016.88   266.5 2014.63   295.1 2013.96   326.1 2010.42   346.9 2000.22
   357.4 1998.66   368.8 1999.49   380.1 1993.28   391.5 1992.39   419.7 1989.95
   426.7 1990.31   433.3  1992.8     477 1999.42   532.4 2001.51   539.8 2003.18
   558.8 2012.89   582.6 2029.66   595.7 2036.07   679.6 2086.59   691.2 2092.18
   716.7 2108.76   746.4 2125.86   756.7 2133.65   806.8 2162.52     831 2178.68
#Mann= 5 ,-1 , 0
       0      .1       0  212.27     .06       0  363.88      .1       0
   391.5    .045       0   433.3      .1       0
Bank Sta=391.5,433.3
XS Rating Curve= 0 ,0
Exp/Cntr=0.3,0.1

Type RM Length L Ch R = 1 ,1079    ,300,300,300
XS GIS Cut Line= 3
     2408310.864      683202.448     2408051.246      682889.128
     2407778.651      682564.557
#Sta/Elev= 30
       0 2240.39    11.1 2231.75      41 2212.47    56.6 2199.82    76.5 2186.24
   124.1 2150.25   139.7 2132.42   181.2 2097.95     228 2064.75   238.4 2055.02
   257.2 2034.74   298.8 1999.92   305.9 1997.61   331.9 1999.11   352.7  1997.4
   360.6 1994.01   373.4 1984.64   388.9 1981.17   394.6 1979.06   408.8 1978.13
   428.7 1980.67   448.6 1981.44   488.2 1985.64   524.7 1985.47   544.5 1993.73
   587.4 2028.21   604.7  2039.7   662.7 2072.51   692.8 2091.87   830.8  2187.8
#Mann= 5 ,-1 , 0
       0      .1       0  253.01     .06       0   388.9    .045       0
   428.7     .06       0   448.6      .1       0
#XS Ineff= 2 , 0
                             491         1992.72
Permanent Ineff=
       F       F
Bank Sta=388.9,428.7
XS Rating Curve= 0 ,0
Exp/Cntr=0.3,0.1

Type RM Length L Ch R = 1 ,779     ,356.8,356.8,356.8
XS GIS Cut Line= 3
     2408536.512       682940.91     2408240.779      682657.657
     2407945.047      682374.403
#Sta/Elev= 30
       0 2194.82    89.7 2128.76   149.8 2086.69   212.9 2044.46   257.2 2016.73
   268.3 2006.78   291.2 1982.03     296  1978.6   342.2 1977.09   362.5 1972.12
   395.7 1971.07   398.7  1969.9   404.4 1967.97   413.5 1967.62   425.1 1967.82
   436.6 1970.53   449.7 1976.41   467.7 1979.97   494.5 1995.46   516.7 2014.19
   537.4 2028.32   592.8 2072.04   627.9 2096.35   679.5 2137.19   709.9 2158.79
   772.3 2195.81   789.4 2203.83   795.2 2205.41   806.7 2202.51     819 2202.57
#Mann= 5 ,-1 , 0
       0      .1       0  210.47     .06       0  333.26      .1       0
   398.7    .045       0   436.6      .1       0
Bank Sta=398.7,436.6
XS Rating Curve= 0 ,0
Exp/Cntr=0.3,0.1

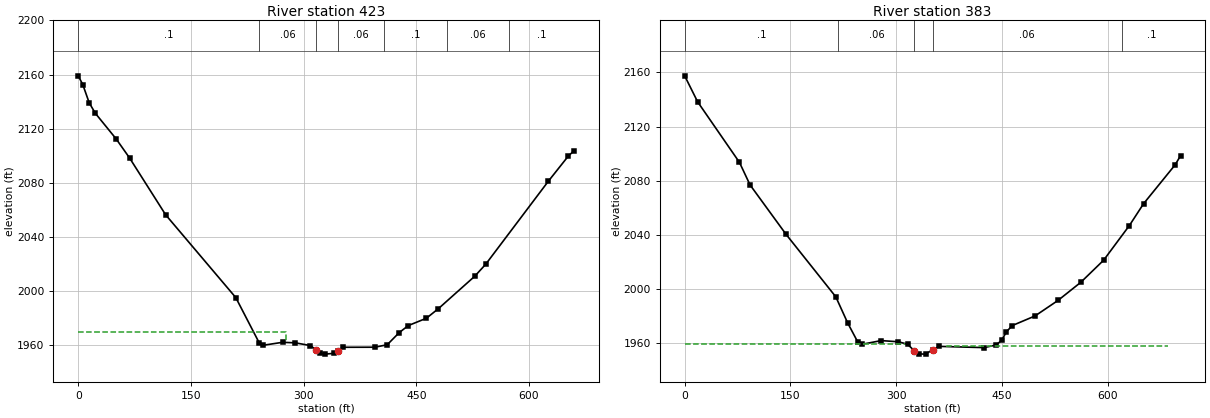
Type RM Length L Ch R = 1 ,423     ,39.3,39.3,39.3
XS GIS Cut Line= 3
 2408739.1097757682643.1119013382408432.44847981682347.960249622
2408199.20976881 682372.95326568
#Sta/Elev= 30
       0 2159.08     6.1  2152.6    14.6 2139.17    22.7 2131.46    50.5 2112.45
    68.3 2098.43   116.4 2056.35   209.8 1995.14   240.9 1961.75   246.5 1959.95
     272  1962.1     289 1961.72   308.8 1959.72   317.21956.393   322.5 1953.91
   328.1 1953.37   339.9 1953.92   345.5 1955.95   352.2 1958.44   394.7 1958.49
   411.3 1960.28   427.3 1969.27   439.4 1974.47   463.5 1979.89   479.6 1987.04
   527.9 2010.96   542.5 2019.82     626 2081.29   652.6 2099.88   660.2 2103.78
#Mann= 7 ,-1 , 0
       0      .1       0  240.66     .06       0   317.2    .045       0
   345.5     .06       0  406.84      .1       0  491.01     .06       0
  573.02      .1       0
#XS Ineff= 2 , 0
             276 1969.67
Permanent Ineff=
       F       F
Bank Sta=317.2,345.5
XS Rating Curve= 0 ,0
Exp/Cntr=0.5,0.3

Type RM Length L Ch R = 1 ,383     ,57.5,57.5,57.5
XS GIS Cut Line= 3
2408760.51819388682628.2036252892408449.44489811682303.408661268
2408198.88071128682343.921718383
#Sta/Elev= 30
       0 2157.49    18.4 2138.24    77.7 2093.47    92.7 2076.83   143.6 2040.39
   214.4 1994.01   231.3 1974.62   245.5 1960.64   251.1 1958.88   278.8 1961.66
   303.3 1960.78   316.2 1958.96   325.71954.146   332.2  1951.8   341.7 1951.65
   351.61954.845   361.1 1957.39   424.7 1956.47   442.1 1958.43   449.7 1961.97
   456.5  1968.2   464.6 1972.76     497 1979.89   529.5 1991.34   561.9 2004.77
   594.3 2021.12   630.8 2046.75     651 2062.95   695.6 2091.58   703.5 2098.48
#Mann= 5 ,-1 , 0
       0      .1       0  218.11     .06       0   325.7    .045       0
   351.6     .06       0  620.22      .1       0
#XS Ineff= 2 ,-1
       0   312.7  1959.5     372   686.2    1958
Permanent Ineff=
       F       F
Bank Sta=325.7,351.6
XS Rating Curve= 0 ,0
Exp/Cntr(USF)=0,0
Exp/Cntr=0.5,0.3