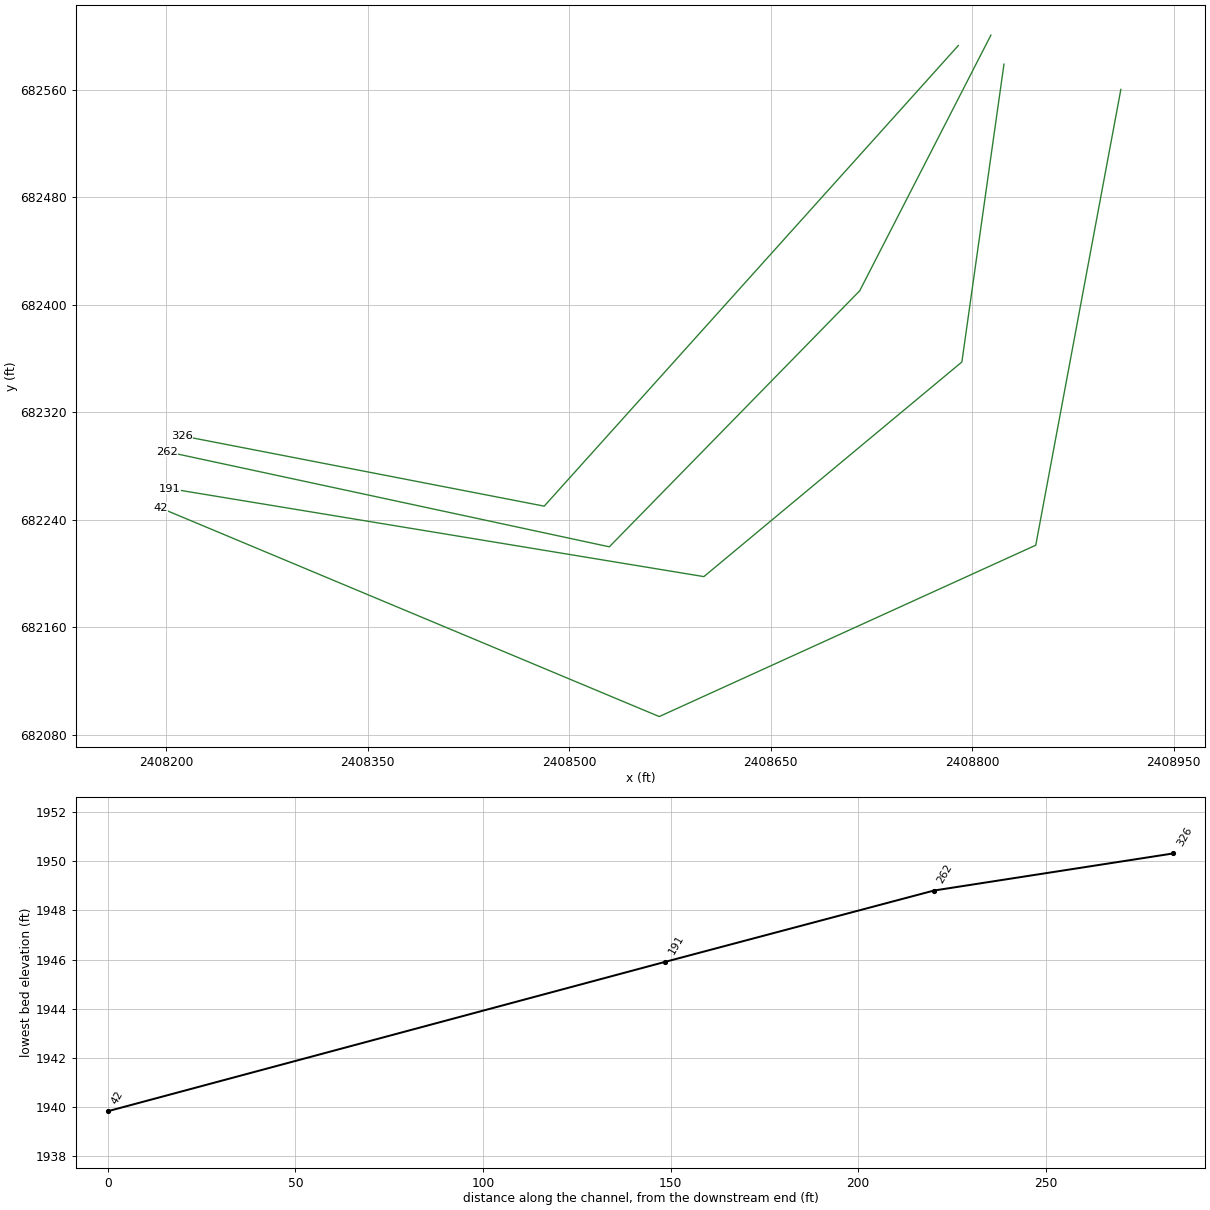
HEC-RAS study HORSCMPRN.prj: HORSCMPRN

--- HORSCMPRN.g01 (geometry) --- (continued)

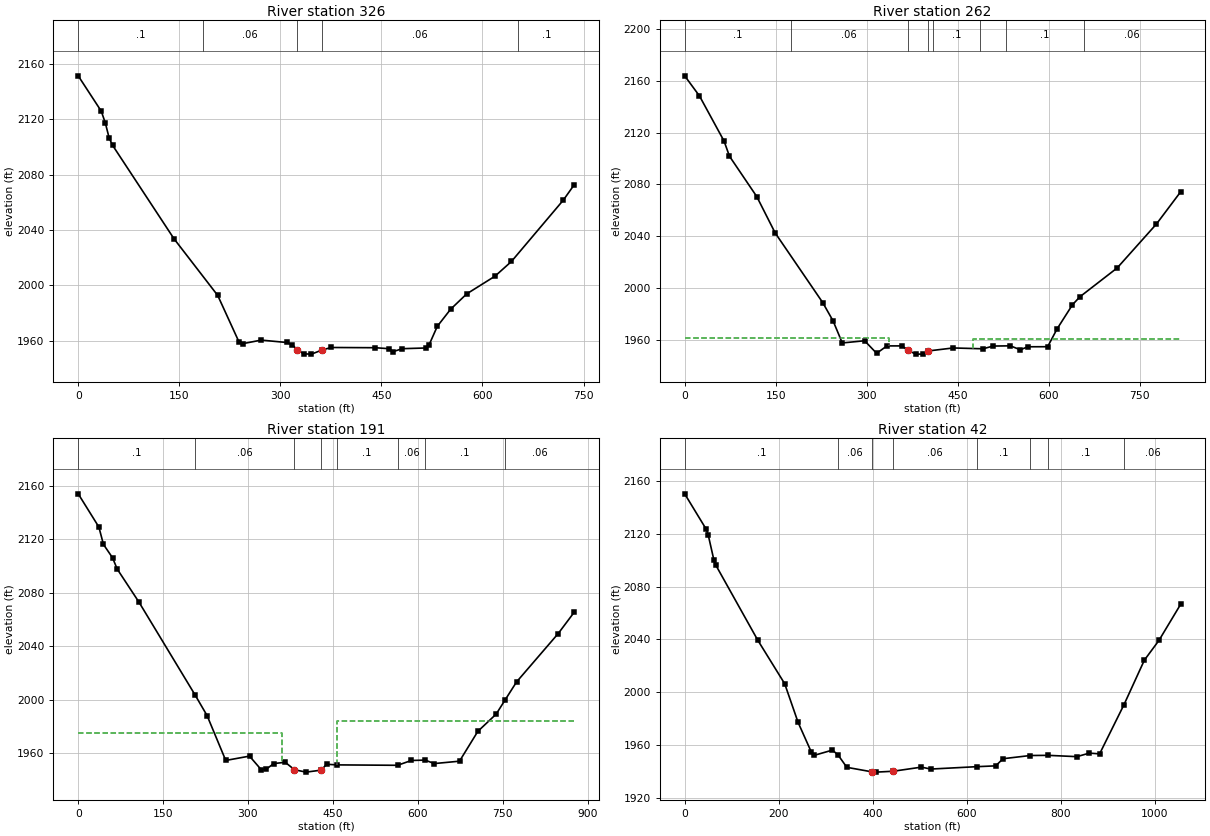
Type RM Length L Ch R = 1 ,326     ,63.8,63.8,63.8
XS GIS Cut Line= 3
 2408789.6029592682592.8905265692408481.35071828682250.012691458
2408211.39704108682302.404920712
#Sta/Elev= 30
       0 2151.26    34.2 2125.75    40.3 2117.12    45.9 2106.43    51.1 2101.02
   142.2  2033.6   207.1 1992.67   238.5 1959.26   244.2 1957.87   271.6 1960.45
   309.3 1958.72   317.8 1957.15   325.4 1953.23   334.8 1950.51   346.2 1950.32
   361.4  1953.2   375.2 1955.11     441 1954.95   461.1 1954.24   467.8 1952.19
   481.1 1954.25   516.7 1954.77   520.8 1957.04     533 1970.42   552.8 1982.75
   576.6 1993.81   618.6  2006.6     643 2017.21     720  2061.5   736.1 2072.55
#Mann= 5 ,-1 , 0
       0      .1       0  184.83     .06       0   325.4    .045       0
   361.4     .06       0   653.4      .1       0
Bank Sta=325.4,361.4
XS Rating Curve= 0 ,0
Exp/Cntr(USF)=0,0
Exp/Cntr=0.5,0.3

Type RM Length L Ch R = 1 ,262     ,71.6,71.6,71.6
XS GIS Cut Line= 4
2408813.82732502682600.5896430962408716.18275185682410.323273574
2408529.81587155682219.7437832812408200.53243548682290.504803256
#Sta/Elev= 30
       0 2163.86    24.4 2148.29    64.9 2113.43    73.8 2101.74   118.8 2070.54
   149.1 2042.46   227.4 1988.69   244.5 1974.51   259.7 1957.45   296.5 1959.14
   316.3 1949.44   333.3 1955.17   358.7 1955.16   367.21951.618   381.4 1948.81
   393.3 1948.83   401.41951.261   442.4 1953.58   491.7 1952.93   508.1 1955.05
   536.7 1955.21   553.1 1952.17   565.4 1954.49   598.1 1954.54   613.6 1968.28
     639 1986.98   651.3 1993.14   712.7 2015.42   777.4 2049.38   817.2  2074.2
#Mann= 8 ,-1 , 0
       0      .1       0     175     .06       0   367.2    .045       0
   401.4     .06       0  409.22      .1       0  486.38     .06       0
  529.67      .1       0  657.19     .06       0
#XS Ineff= 2 , 0
          336.59 1961.42  475.55         1960.32
Permanent Ineff=
       F       F
Bank Sta=367.2,401.4
XS Rating Curve= 0 ,0
Exp/Cntr(USF)=0,0
Exp/Cntr=0.3,0.1

Type RM Length L Ch R = 1 ,191     ,148.6,148.6,148.6
XS GIS Cut Line= 4
2408823.56229613682579.0031578582408792.21614393682357.316938479
  2408600.190323682197.5710109062408202.78753898682263.040541339
#Sta/Elev= 30
       0 2154.15    36.5 2129.31    44.6 2116.29    60.7 2106.29    68.8 2097.92
   107.4 2073.08   206.1 2003.95   227.7 1988.25   260.7 1954.65   302.7 1957.89
   323.2 1947.84   331.8 1947.96   345.5  1952.3   365.8 1953.29   382.2  1947.7
   402.7 1945.91   429.11947.382   439.1  1951.8   456.7 1951.33   564.3 1951.02
   588.7 1954.63     613 1954.91   629.2 1952.31   673.8  1954.1   706.2 1976.42
   738.6 1989.33   754.5    2000   774.7 2013.44   848.1 2049.54   876.4 2065.51
#Mann= 8 ,-1 , 0
       0      .1       0   206.1     .06       0   382.2    .045       0
   429.1     .06       0   456.7      .1       0   564.3     .06       0
     613      .1       0   754.5     .06       0
#XS Ineff= 2 , 0
          359.33 1975.45  457.49         1984.51
Permanent Ineff=
       F       F
Bank Sta=382.2,429.1
XS Rating Curve= 0 ,0
Exp/Cntr(USF)=0,0
Exp/Cntr=0.3,0.1

Type RM Length L Ch R = 1 ,42      ,,,
XS GIS Cut Line= 4
 2408910.5565192682560.1842273462408847.21951289682220.940810011
2408566.97495075682093.3991671772408195.62921515682248.704977159
#Sta/Elev= 30
       0 2149.99    46.1 2123.09    50.1 2118.92    62.4 2099.66    66.4 2096.04
   155.9 2039.25   212.9 2006.56   241.4 1977.37   269.9 1954.69   275.3 1952.47
   314.6 1956.48   326.7 1952.64   345.1 1943.46   398.3 1940.06   407.2 1939.83
   443.7 1940.49   503.8  1943.6   523.9 1942.15   621.9 1943.95   661.9 1944.56
   677.6 1949.96   735.6 1952.38   773.6  1952.5   834.7 1951.52   861.4  1954.2
   883.1 1953.61   935.1 1990.85   978.4 2024.41  1009.4 2039.291055.522 2066.54
#Mann= 8 ,-1 , 0
       0      .1       0   326.7     .06       0   398.3    .045       0
   443.7     .06       0   621.9      .1       0   735.6     .06       0
   773.6      .1       0   935.1     .06       0
Bank Sta=398.3,443.7
XS Rating Curve= 0 ,0
Exp/Cntr(USF)=0,0
Exp/Cntr=0.3,0.1
LCMann Table=0

Chan Stop Cuts=-1
Use User Specified Reach Order=0
Composite Channel Slope=5